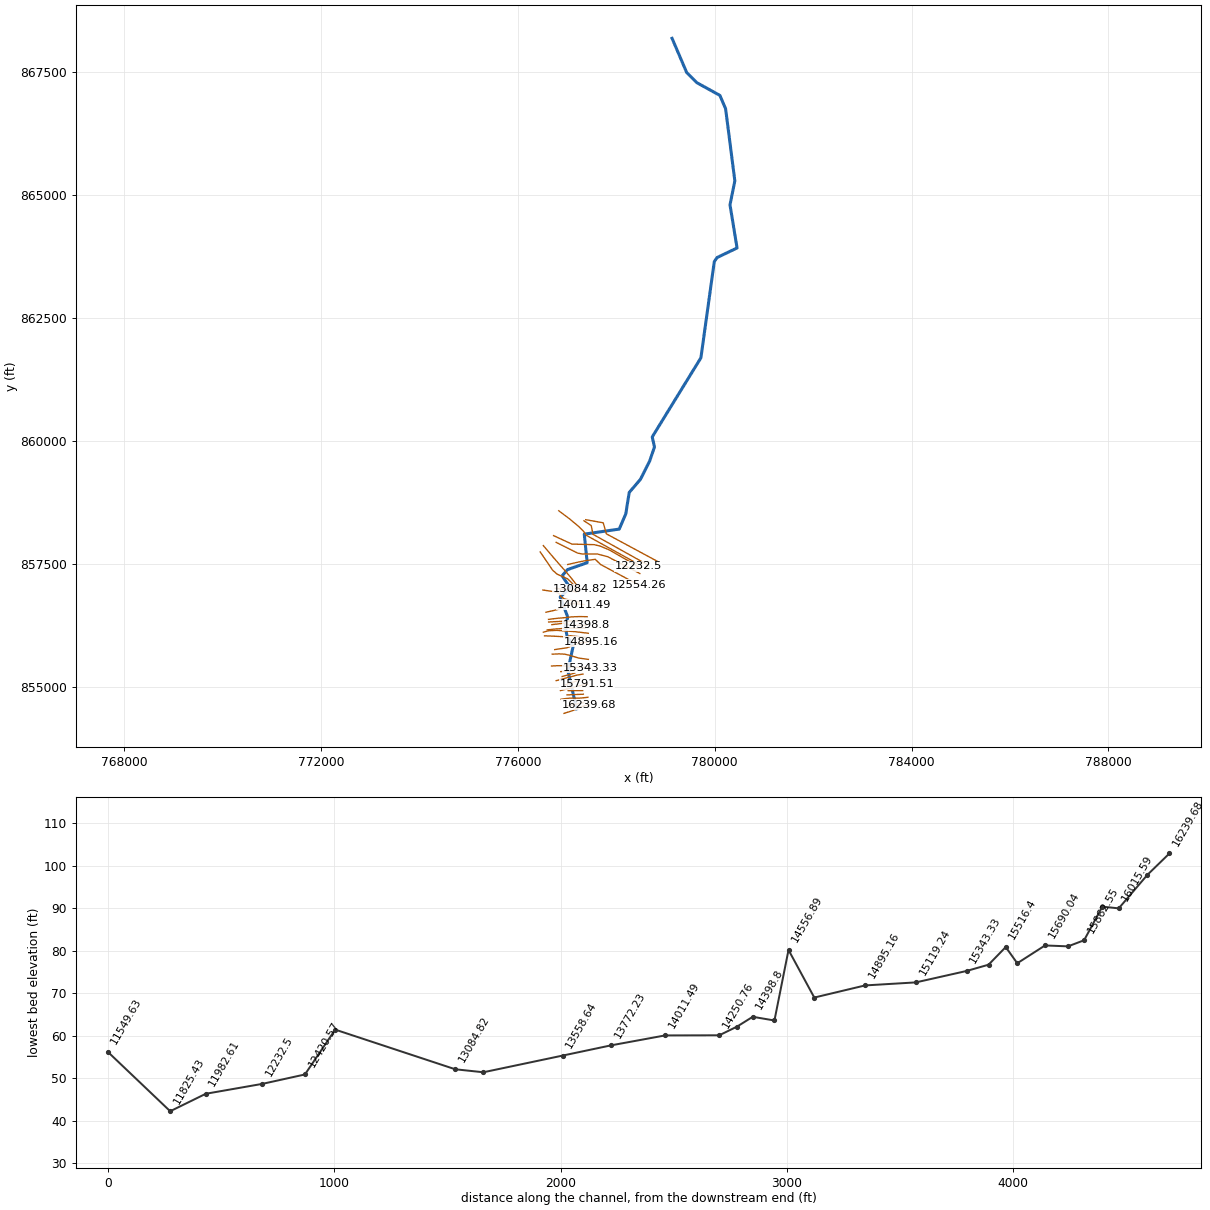
--- 16031_ras.prj (project) ---

Proj Title=16031
Current Plan=p01
Default Exp/Contr=0.3,0.1
English Units
Geom File=g01
Flow File=f01
Plan File=p01
Y Axis Title=Elevation
X Axis Title(PF)=Main Channel Distance
X Axis Title(XS)=Station
BEGIN DESCRIPTION:
RFD model 16031 exported to HEC-RAS
END DESCRIPTION:

--- 16031_ras.p01 (plan) ---

Plan Title=Plan 01
Program Version=4.10
Short Identifier=Plan 01
Geom File=g01
Flow File=f01
Subcritical Flow
Calc Critical at every XS
Secant Critical Depth

--- 16031_ras.f01 (steady flow) ---

Flow Title=Flow 01
Program Version=5.01
Number of Profiles= 6
Profile Names=10yr,25yr,50yr,100yr,100plus,500yr
River Rch & RM=16031,65,16239.68
  282.33  460.16  629.02  786.34 1148.05 1888.92
River Rch & RM=16031,65,16142.38
  285.05  464.61  635.11  793.97 1159.19 1904.64
River Rch & RM=16031,65,16015.59
  285.73  465.72  636.64  795.87 1161.97 1908.57
River Rch & RM=16031,65,15943.04
  287.43  468.49  640.44  800.63 1168.92 1918.36
River Rch & RM=16031,65,15862.55
  289.81  472.38  645.76  807.28 1178.63 1932.03
River Rch & RM=16031,65,15690.04
  292.86  477.35  652.58  815.81 1191.09 1949.56
River Rch & RM=16031,65,15567.42
  293.53  478.46  654.09  817.71 1193.85 1953.45
River Rch & RM=16031,65, 15516.4
  294.55  480.12  656.36  820.55    1198 1959.27
River Rch & RM=16031,65,15343.33
  361.67  589.95  807.03 1009.16 1473.37 2341.03
River Rch & RM=16031,65,15119.24
  413.28  674.38  922.87 1154.16 1685.07 2627.43
River Rch & RM=16031,65,14895.16
  421.13  687.23  940.49 1176.21 1717.27 2670.52
River Rch & RM=16031,65,14670.71
  430.19  702.05  960.84 1201.69 1754.46 2720.16
River Rch & RM=16031,65,14494.64
  433.93  708.17  969.24  1212.2 1769.81  2740.6
River Rch & RM=16031,65, 14398.8
  437.66  714.28  977.62 1222.69 1785.13 2760.98
River Rch & RM=16031,65,14250.76
  439.53  717.33  981.81 1227.93 1792.78 2771.15
River Rch & RM=16031,65,14011.49
  451.91   737.6 1009.63 1262.75 1843.62 2838.56
River Rch & RM=16031,65,13772.23
  454.38  741.64 1015.17 1269.69 1853.75 2851.97
River Rch & RM=16031,65,13558.64
  456.85  745.68 1020.71 1276.63 1863.88 2865.35
River Rch & RM=16031,65,13209.05
  843.35 1379.54 1892.07 2368.42  3457.9 4877.05
River Rch & RM=16031,65,12554.26
  854.93 1398.56 1918.25 2401.25 3505.83 4935.23
River Rch & RM=16031,65,12420.57
  857.89 1403.42 1924.95 2409.64 3518.08 4950.07
River Rch & RM=16031,65, 12232.5
  860.04 1406.95  1929.8 2415.73 3526.97 4960.85
River Rch & RM=16031,65,11982.61
  888.24 1453.24 1993.49 2495.55 3643.51 5101.52
River Rch & RM=16031,65,11825.43
   890.1  1456.3  1997.7 2500.84 3651.22 5110.85
River Rch & RM=16031,65,11549.63
 1034.86 1694.45 2325.87 2912.67  4252.5  5829.2
River Rch & RM=16031,65, 11194.2
 1145.66    1877 2577.69 3228.94 4714.25 6372.02
River Rch & RM=16031,65, 10763.7
 1155.93 1893.94 2601.06 3258.29  4757.1 6422.01
River Rch & RM=16031,65,10642.72
 1159.68 1900.12 2609.59 3269.01 4772.75 6440.26
River Rch & RM=16031,65,10576.46
 1160.68 1901.76 2611.86 3271.86 4776.92 6445.12
River Rch & RM=16031,65,10351.83
 1218.97 1997.71 2744.14 3437.88  5019.3 6725.96
River Rch & RM=16031,65,10111.58
 1225.38 2008.28 2758.74 3456.23 5046.09 6757.01
River Rch & RM=16031,65,9871.332
 1288.77 2113.03 2903.53 3638.38 5312.03 7064.52
River Rch & RM=16031,65,9631.083
 1292.66 2119.45 2912.41 3649.54 5328.32 7083.27
River Rch & RM=16031,65,9406.903
  1324.1 2171.41 2984.23 3739.88 5460.23  7234.9
River Rch & RM=16031,65,9278.589
 1324.82  2172.6 2985.88 3741.96 5463.26 7238.39
River Rch & RM=16031,65,9223.784
 1325.78 2174.19 2988.07 3744.73  5467.3 7243.03
River Rch & RM=16031,65,9120.828
  1326.5 2175.38 2989.72  3746.8 5470.33 7246.52
River Rch & RM=16031,65,8914.517
 1330.35 2181.75 2998.53 3757.88 5486.51 7265.08
River Rch & RM=16031,65,8686.985
 1336.55 2192.02 3012.76 3775.81 5512.69 7295.21
River Rch & RM=16031,65,8459.453
 1338.46 2195.18 3017.14 3781.32 5520.73 7304.47
River Rch & RM=16031,65,8180.058
 1341.56 2200.31 3024.24 3790.28  5533.8 7319.51
River Rch & RM=16031,65,8005.304
 1342.27  2201.5 3025.88 3792.34 5536.82 7322.97
River Rch & RM=16031,65,7723.268
  1428.2 2343.88 3223.06 4040.77 5899.52 7738.07
River Rch & RM=16031,65,7478.615
 1430.77 2348.14 3228.96 4048.22  5910.4 7750.51
River Rch & RM=16031,65,7233.962
 1437.52 2359.37 3244.53 4067.86 5939.07 7783.27
River Rch & RM=16031,65, 6989.31
 1477.99 2426.65 3337.93 4185.77 6111.22 7979.83
River Rch & RM=16031,65,6913.878
 1478.68  2427.8 3339.52 4187.78 6114.16 7983.18
River Rch & RM=16031,65,6747.744
 1479.37 2428.95 3341.12  4189.8 6117.11 7986.53
River Rch & RM=16031,65,6509.533
 1486.53 2440.84 3357.62 4210.63 6147.52 8021.14
River Rch & RM=16031,65,6345.646
 1487.68 2442.76 3360.29 4213.99 6152.42 8026.72
River Rch & RM=16031,65,6125.208
 1489.06 2445.06 3363.47 4218.01  6158.3 8033.41
River Rch & RM=16031,65,5904.078
 1578.71 2594.66 3571.62 4481.34 6542.75 8471.35
River Rch & RM=16031,65,5682.948
 1580.06 2596.92 3574.76  4485.3 6548.54  8477.9
River Rch & RM=16031,65,5019.557
 2844.18 4680.85 6452.36 8098.6811824.0714083.27
River Rch & RM=16031,65,4883.414
  2848.7 4688.43 6462.95 8112.1111843.6814103.83
River Rch & RM=16031,65,4530.894
 2858.71 4705.22  6486.4 8141.8611887.1114149.38
River Rch & RM=16031,65,4197.221
 2864.97 4715.73 6501.09  8160.511914.3214177.93
River Rch & RM=16031,65,3976.877
 2868.49 4721.64 6509.35 8170.9711929.6214193.98
River Rch & RM=16031,65,3728.529
 2870.83 4725.58 6514.85 8177.9511939.8114204.68
River Rch & RM=16031,65,3480.181
 2888.51 4755.31 6556.44 8230.7712016.9214285.69
Boundary for River Rch & Prof#=16031,65,1
Up Type= 0
Dn Type= 2
Boundary for River Rch & Prof#=16031,65,2
Up Type= 0
Dn Type= 2
Boundary for River Rch & Prof#=16031,65,2
Up Type= 0
Dn Type= 2
Boundary for River Rch & Prof#=16031,65,2
Up Type= 0
Dn Type= 2
Boundary for River Rch & Prof#=16031,65,2
Up Type= 0
Dn Type= 2
Boundary for River Rch & Prof#=16031,65,2
Up Type= 0
Dn Type= 2

--- 16031_ras.g01 (geometry) ---

Geom Title=16031
Program Version=4.10

River Reach=16031,65
Reach XY= 30
777193.313987017854563.010790035777015.637847751 855339.71967642
 777122.24335584855827.807483926776999.279307425856039.854281798
776961.269720763856243.509816751 777014.31589663856425.444514737
776860.535482407856834.863272622777062.656716764857024.304391026
776899.162588865857265.730043262777006.190335572 857391.02987878
777408.934379756857532.925468907 777349.33037281858112.777501896
778059.710448623858215.591493383778193.470428318858526.386740327
778262.375059366858959.304596826 778489.96940884 859225.15398553
778679.282203078 859599.84134303778775.683399469859884.528717875
778730.656542093860088.514987037779719.747484505861696.110703558
779991.465619355863650.541995257780047.383341849863733.629808545
780454.460884273863928.057531431780311.028374225864804.639997274
780409.313151121865291.976355642780221.870808184866756.706895873
 780105.25364247867029.330859199779639.010109544867286.740146518
779431.141120553867493.885294065779133.595387071868188.848543078

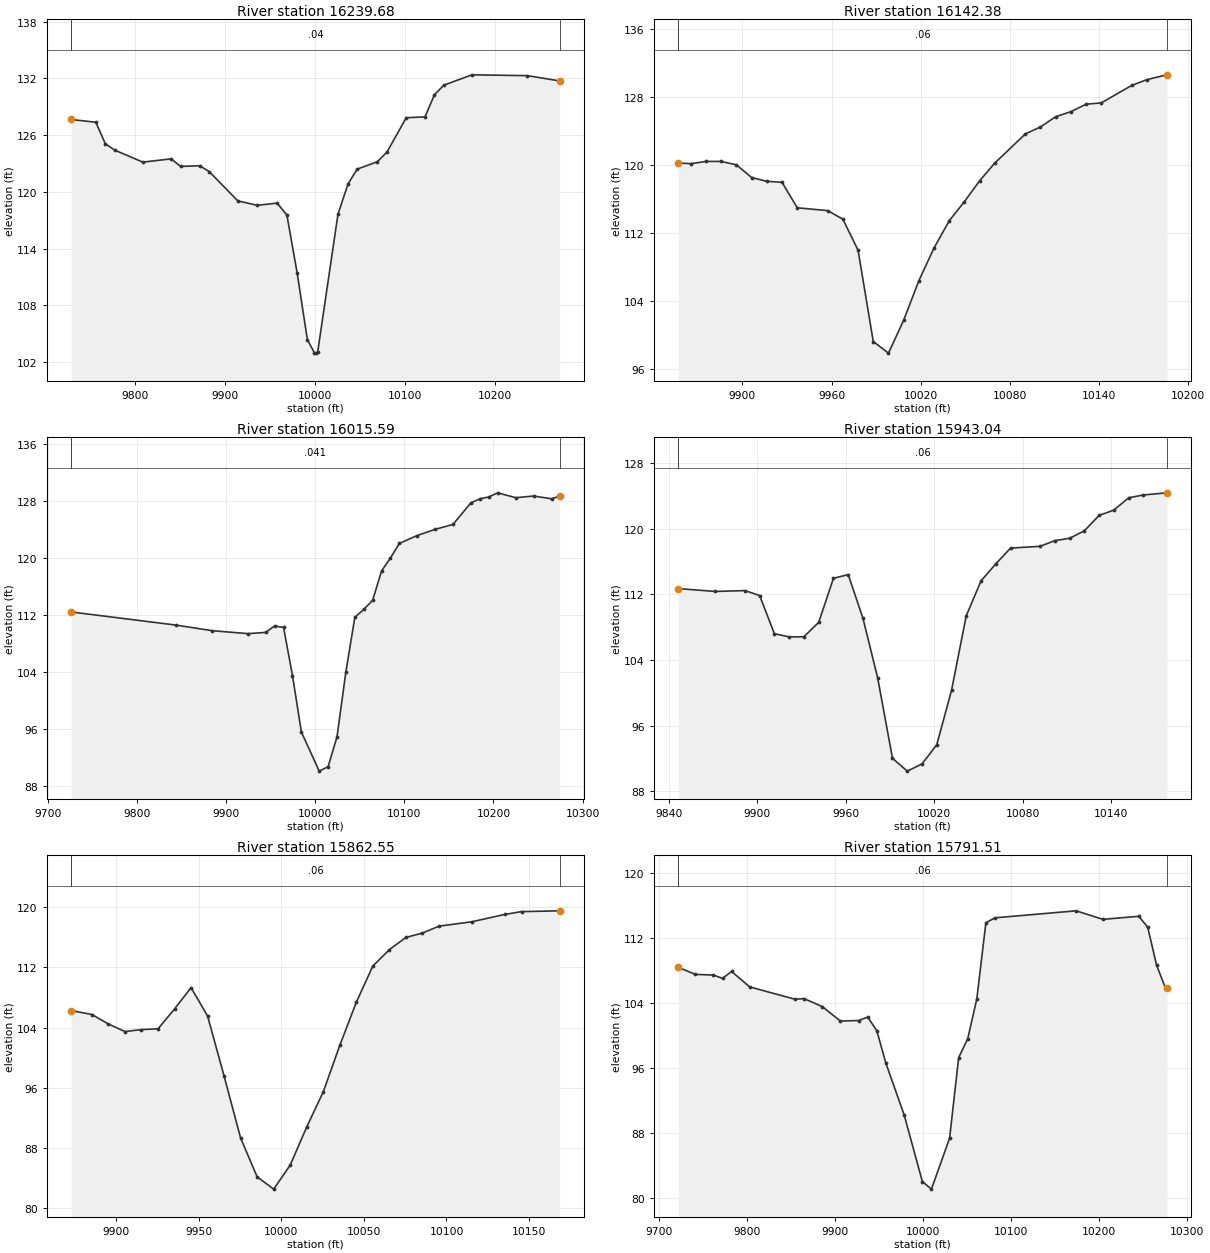
Type RM Length L Ch R = 1 ,16239.68,97.297800,97.297800,97.297800
XS GIS Cut Line= 6
776938.534900627854470.489685906777113.587700828854526.267052311
777229.537066109854583.167174923777280.701137707854603.378958672
777351.327391625854624.488574567777449.982961402854647.440913823
#Sta/Elev= 30
9728.456127.65269756.042127.36049766.465125.08899776.888124.41869808.158123.1461
9839.568123.49169850.163122.69299871.354122.76399881.949122.1521 9913.78119.0465
  9935.6118.5788 9957.42118.8188 9968.33117.54889979.708111.44999991.096104.3799
    9999102.9763   10001102.957610002.52103.0556 10025.1 117.64110036.38120.8661
10046.49122.405310068.88123.186710079.63124.2194   10101 127.83910121.88127.9325
10132.31130.264710142.75131.2798   10174132.3742 10235.6132.287110271.52131.7307
#Mann= 3 , 0 , 0
9728.456    0.04       09728.456    0.04       010271.52    0.04       0
#XS Ineff= 2 , 0
       0                               0
Bank Sta=9728.456,10271.52
Exp/Cntr=0.3,0.1

Type RM Length L Ch R = 1 ,16142.38,126.789500,126.789500,126.789500
XS GIS Cut Line= 2
777016.773561984854623.598300278777338.163058668854692.697042063
#Sta/Elev= 30
9856.877120.25959865.292120.1786 9875.52120.44289885.749120.44199895.977120.0399
9906.206118.55029916.434118.10429926.663117.98869936.891114.99289957.348114.6638
9967.577113.65519977.805110.02199988.03499.286349998.26297.9231210008.49101.7884
10018.72106.426510028.95110.291310039.18 113.47610049.41115.729210059.63118.1718
10069.86120.258910090.32123.666110100.55 124.49310110.78125.6933   10121126.2878
10131.23127.161610141.46127.320210161.92129.366810172.15130.050610185.61130.6145
#Mann= 3 , 0 , 0
9856.877    0.06       09856.877    0.06       010185.61    0.06       0
#XS Ineff= 2 , 0
       0                               0
Bank Sta=9856.877,10185.61
Exp/Cntr=0.3,0.1

Type RM Length L Ch R = 1 ,16015.59,72.555000,72.555000,72.555000
XS GIS Cut Line= 6
776878.027076688854756.520817714776964.414167808854770.574010093
777034.165763242854778.290089362 777095.77685706854781.071106488
777256.771148945854779.863792988777424.038852528854797.342318468
#Sta/Elev= 30
9725.692112.38579843.987 110.5329884.227 109.7529924.268109.33999944.288 109.513
 9954.29110.42859964.292110.20329974.294103.44679984.29695.52621 10004.390.02804
10014.3190.6557810024.3194.8500410034.31104.019210044.32111.625310054.32112.7421
10064.32114.024810074.33118.152210084.33 119.96510094.33122.010110114.36123.1232
10134.43123.9858 10154.5 124.67810174.57 127.701 10184.6128.274910194.67128.5369
10204.75129.1178 10224.9128.435410245.06 128.66810265.21128.284710274.32128.6552
#Mann= 3 , 0 , 0
9725.692   0.041       09725.692   0.041       010274.32   0.041       0
#XS Ineff= 2 , 0
       0                               0
Bank Sta=9725.692,10274.32
Exp/Cntr=0.3,0.1

Type RM Length L Ch R = 1 ,15943.04,80.484700,80.484700,80.484700
XS GIS Cut Line= 2
776999.900613368854846.160526752777330.931795031854859.819580376
#Sta/Elev= 30
9846.447112.70739871.568112.36039891.585112.46629901.593111.85939911.602107.2006
 9921.61106.81419931.619106.83189941.627 108.5879951.636113.96429961.644114.4187
9971.653109.08539981.661101.7749 9991.6792.0008910001.6890.4314310011.6991.30872
 10021.793.64865 10031.7100.279310041.71109.401610051.72113.648110061.73115.7302
10071.74 117.65310091.75 117.86810101.76 118.56310111.77118.848710121.78119.7594
10131.79121.6415 10141.8122.286610151.81123.792410161.81 124.13610177.76124.3969
#Mann= 3 , 0 , 0
9846.447    0.06       09846.447    0.06       010177.76    0.06       0
#XS Ineff= 2 , 0
       0                               0
Bank Sta=9846.447,10177.76
Exp/Cntr=0.3,0.1

Type RM Length L Ch R = 1 ,15862.55,71.047600,71.047600,71.047600
XS GIS Cut Line= 2
 777022.39787817854932.132217124777318.076215118854933.739164606
#Sta/Elev= 27
9872.807106.27579885.409 105.7459895.409104.48399905.409103.4808 9915.41103.7401
 9925.41103.8426 9935.41106.4849 9945.41109.3202 9955.41105.5505 9965.4197.55428
 9975.4189.311459985.41184.153789995.41182.5202410005.4185.7122510015.4190.79089
10025.4195.4459810035.41101.634310045.41107.369910055.41112.191410065.41114.3707
10075.41115.995610085.41116.580710095.41117.497710115.41118.084410135.41119.0669
10145.41119.431610168.49119.5378
#Mann= 3 , 0 , 0
9872.807    0.06       09872.807    0.06       010168.49    0.06       0
#XS Ineff= 2 , 0
       0                               0
Bank Sta=9872.807,10168.49
Exp/Cntr=0.3,0.1

Type RM Length L Ch R = 1 ,15791.51,101.467000,101.467000,101.467000
XS GIS Cut Line= 6
776866.157328643854934.207201552776999.188017043854966.231771456
777134.307089113855002.082721316777238.165899275855028.276881149
777317.473782647855045.225765093777406.510547839855060.906940488
#Sta/Elev= 30
9722.375108.39499741.756107.53979762.327107.45159772.613107.04899782.898 107.897
 9803.47105.99539854.898104.47769865.219104.55299885.911103.57459906.603101.7883
9927.295101.85369937.641102.27979947.987100.58389958.33396.573449979.02590.22515
9999.71682.0209710010.0381.0872410030.6687.3572810040.9797.2824510051.2899.61285
10061.59104.518810071.91113.895310082.22114.504510174.45115.365310205.01 114.316
10245.62114.693610255.78113.355610265.93 108.66410276.08105.831310277.62105.8021
#Mann= 3 , 0 , 0
9722.375    0.06       09722.375    0.06       010277.62    0.06       0
#XS Ineff= 2 , 0
       0                               0
Bank Sta=9722.375,10277.62
Exp/Cntr=0.3,0.1

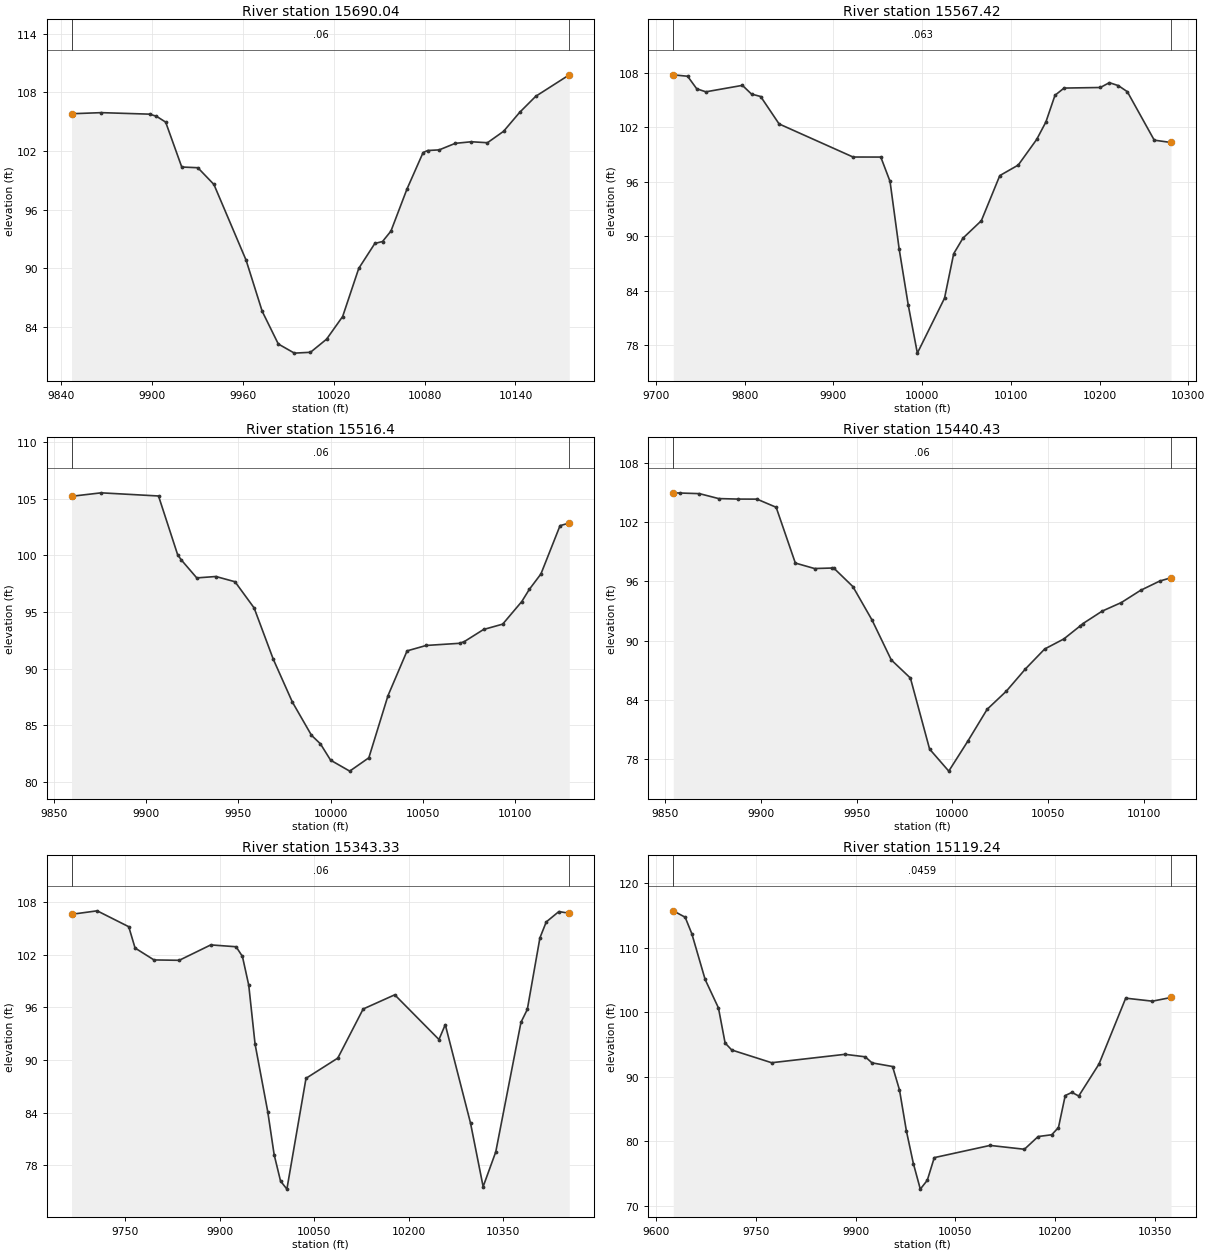
Type RM Length L Ch R = 1 ,15690.04,122.620300,122.620300,122.620300
XS GIS Cut Line= 2
776956.513031334855046.225488454777265.850421935 855156.30139108
#Sta/Elev= 30
9847.147105.80839866.769105.92129898.612105.76699903.148105.55039909.226104.9519
9919.841100.35459930.455100.28279941.06998.567879962.298 90.81259972.91285.58302
9983.52682.239429994.14181.3028510004.7581.3891710015.3782.7300410025.9885.05067
 10036.6 89.976610047.2192.5295410052.2992.7298810057.8393.7939110068.4498.11145
10079.05101.837110082.12102.044910089.67102.109510100.28102.7792 10110.9102.9409
10121.51102.842210132.13104.009410142.74105.949110153.35 107.59510175.49109.7926
#Mann= 3 , 0 , 0
9847.147    0.06       09847.147    0.06       010175.49    0.06       0
#XS Ineff= 2 , 0
       0                               0
Bank Sta=9847.147,10175.49
Exp/Cntr=0.3,0.1

Type RM Length L Ch R = 1 ,15567.42,51.015200,51.015200,51.015200
XS GIS Cut Line= 6
 776779.27462582855135.878581114776877.247944731855159.779066185
777019.551276546855201.582843311777078.344246578855214.031870915
777186.299629703855244.658761268777323.667492348855269.761504308
#Sta/Elev= 30
9719.406107.76359735.592107.60759745.886106.22369756.179105.89239797.352106.6025
9807.645105.64459817.938105.37549838.754102.35329922.13598.709949953.40398.70515
9963.82596.020289974.14788.558679984.38482.389339994.62177.1103510025.2583.16289
10035.5988.0643310045.9889.7678510066.7791.6962510087.5696.6648610108.3597.82317
10129.14100.646310139.53102.568110149.78105.507610160.01106.304410200.93106.3684
 10211.1106.899610221.22106.574810231.34105.9073 10261.7100.568310280.59100.3107
#Mann= 3 , 0 , 0
9719.406   0.063       09719.406   0.063       010280.59   0.063       0
#XS Ineff= 2 , 0
       0                               0
Bank Sta=9719.406,10280.59
Exp/Cntr=0.3,0.1

Type RM Length L Ch R = 1 , 15516.4,75.979000,75.979000,75.979000
XS GIS Cut Line= 2
776899.514390379855219.245418496777159.839882702855290.754581504
#Sta/Elev= 28
9859.552105.23839875.611105.54539906.722105.26599917.093100.0705 9919.03 99.6174
9927.46398.017729937.83398.141719948.20497.677749958.57495.360589968.94590.83028
9979.31587.033999989.68584.092619994.53683.3360910000.0681.8889710010.4380.92083
 10020.882.1014410031.1787.5934710041.5491.5610110051.91 92.040410070.0492.23139
10072.65 92.389910083.0293.4540510093.3993.9270610103.7695.9289610107.7996.99348
10114.1398.36528 10124.5102.640110129.52102.8737
#Mann= 3 , 0 , 0
9859.552    0.06       09859.552    0.06       010129.52    0.06       0
#XS Ineff= 2 , 0
       0                               0
Bank Sta=9859.552,10129.52
Exp/Cntr=0.3,0.1

Type RM Length L Ch R = 1 ,15440.43,97.093100,97.093100,97.093100
XS GIS Cut Line= 2
776871.344814718855318.603086933777130.866833299855338.689930469
#Sta/Elev= 30
9854.059104.98489857.725104.96489867.755104.90219877.785104.40229887.815104.3511
9897.845 104.3469907.875 103.5199917.90597.864029927.93497.309839936.954 97.3586
9937.96497.362589947.99495.479089958.02492.083769968.054 88.04849978.08486.20341
9988.11479.003959998.14476.7673310008.1779.82706 10018.283.0331910028.2384.87166
10038.2687.1343910048.2989.1488410058.3290.1695910066.54  91.43910068.3591.73341
10078.3892.9923210088.4193.8616110098.4495.0965710108.4796.0399110114.3696.37201
#Mann= 3 , 0 , 0
9854.059    0.06       09854.059    0.06       010114.36    0.06       0
#XS Ineff= 2 , 0
       0                               0
Bank Sta=9854.059,10114.36
Exp/Cntr=0.3,0.1

Type RM Length L Ch R = 1 ,15343.33,224.087300,224.087300,224.087300
XS GIS Cut Line= 6
776684.436674237855433.570569634776799.015653819855439.465183645
776904.398605019 855438.24586153776973.221544981855432.640414819
777145.476531655855410.965860546777471.539699793855398.146987364
#Sta/Elev= 30
9665.374106.60329705.991     1079756.057105.1897 9766.07102.76349796.089101.4056
9836.092101.36339886.097103.1178 9926.23102.90819936.263101.81169946.29698.53295
9956.33991.815099976.51484.083899986.60279.213479996.68976.2222710006.7875.29453
10037.0987.9190910087.4990.22128 10127.795.8155410177.7997.4323710247.8992.33883
10257.8994.0359410297.9182.8215810317.9275.5751910337.9379.5350510377.9594.30815
10387.9695.7662910407.96103.920610417.97105.733510437.98106.915110454.53106.7229
#Mann= 3 , 0 , 0
9665.374    0.06       09665.374    0.06       010454.53    0.06       0
#XS Ineff= 2 , 0
       0                10148.97       0
Bank Sta=9665.374,10454.53
Exp/Cntr=0.3,0.1

Type RM Length L Ch R = 1 ,15119.24,224.087300,224.087300,224.087300
XS GIS Cut Line= 6
776697.120125927855673.651296622 776845.59956874855679.834861319
776954.502304659855672.524830647777027.886338005855656.790973231
777242.643690873855593.594492574 777432.75034355855567.270643192
#Sta/Elev= 30
9625.536115.70639643.447114.71569653.465112.16339673.501105.07719693.537100.6719
9703.55595.237219713.55894.153879773.571  92.1849883.89493.484879914.38193.09913
9924.60592.161739955.504 91.59669965.91187.983019976.36281.600719986.81276.57344
9997.26372.6085610007.7673.9797710018.2677.4865110102.2579.37664 10153.978.78217
10174.5480.7519510194.98 81.028610205.1482.14882 10215.387.0979610225.4687.59156
10235.6187.0269610266.0691.97172 10306.3102.181510346.54101.715610374.45102.2878
#Mann= 3 , 0 , 0
9625.536  0.0459       09625.536  0.0459       010374.45  0.0459       0
#XS Ineff= 2 , 0
       0                10127.08       0
Bank Sta=9625.536,10374.45
Exp/Cntr=0.3,0.1

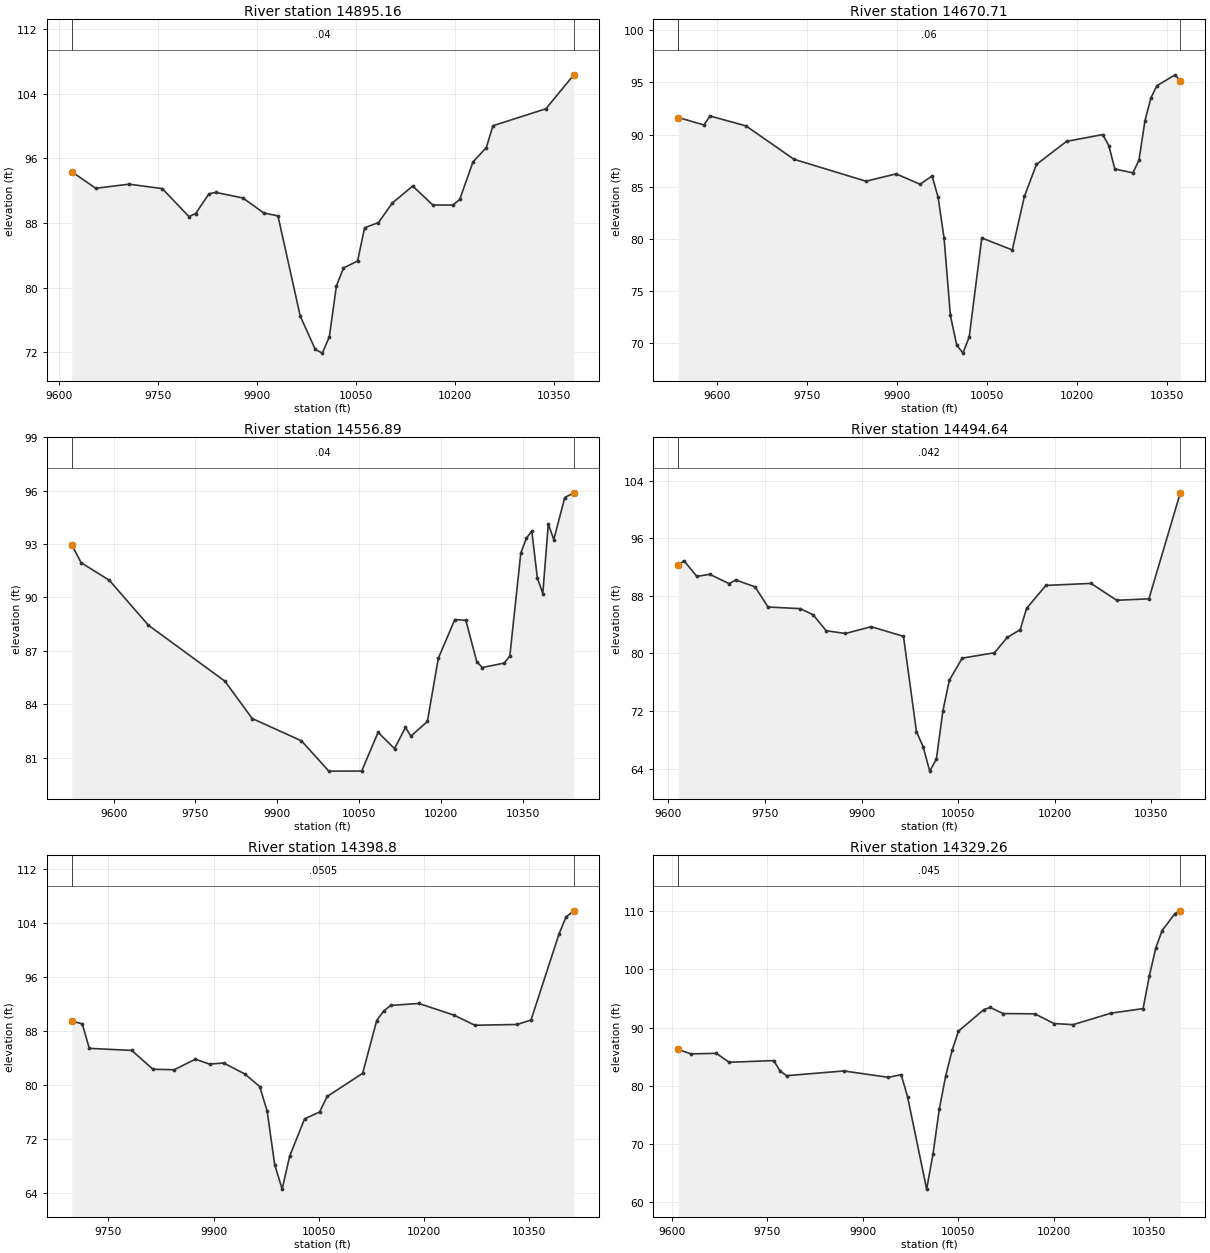
Type RM Length L Ch R = 1 ,14895.16,224.451800,224.451800,224.451800
XS GIS Cut Line= 6
776748.955976557855766.212499043777000.425058799855804.316250727
777170.110376861855874.592959703 777257.79713013 855899.38847648
777371.027402071855916.225825409777487.284058718855923.979468412
#Sta/Elev= 30
9619.58594.355719655.92392.304599706.33292.814339756.74192.265549797.187 88.7963
9807.32989.182889827.61291.630449837.75491.790839878.88291.10755 9910.4689.25597
9932.06188.883769965.80376.48059 9988.5872.369269999.266 71.8956 10009.973.91977
10020.61 80.208610031.3282.4317910052.7383.3067810063.3487.4200510084.3788.05979
10105.3390.4816410136.2192.5821310166.8690.2276110197.3590.2333710207.4490.91823
10227.5995.5731310247.7597.3423810257.83100.049210338.04102.150310380.42106.3525
#Mann= 3 , 0 , 0
9619.585    0.04       09619.585    0.04       010380.42    0.04       0
#XS Ineff= 2 , 0
       0                               0
Bank Sta=9619.585,10380.42
Exp/Cntr=0.3,0.1

Type RM Length L Ch R = 1 ,14670.71,113.818700,113.818700,113.818700
XS GIS Cut Line= 5
 776542.07091403856046.402560622776745.540404618856038.169691071
776984.411891133856025.365053073777059.565572202856048.754809067
777373.590739697856014.647206604
#Sta/Elev= 30
 9534.9691.632689577.92490.920859587.93291.779169647.98190.828679728.04787.62789
9848.212  85.5269898.284  86.2319938.34285.23606 9958.3786.029069968.38583.99482
9978.42680.034179988.89972.655429999.37269.8284110009.8569.0421110020.3270.59778
10041.2680.0836910092.16 78.936810112.2884.06489 10132.487.1354310182.6989.34664
10243.0489.99848 10253.188.9488310263.1686.6954210293.3486.33066 10303.487.53544
10313.4691.3301410323.5193.5453610333.5794.6925810363.7595.7268710372.3995.12238
#Mann= 3 , 0 , 0
 9534.96    0.06       0 9534.96    0.06       010372.39    0.06       0
#XS Ineff= 2 , 0
       09960.073        10092.51       0
Bank Sta=9534.96,10372.39
Exp/Cntr=0.3,0.1

Type RM Length L Ch R = 1 ,14556.89,62.245800,62.245800,62.245800
XS GIS Cut Line= 5
776518.517156112856120.744642388776623.061784766856149.256813822
776788.231628299856157.574719616777161.197266716856131.087207054
777431.482843888856098.679527811
#Sta/Elev= 30
9523.33592.96417 9540.42 91.95179592.24690.959279663.67788.438569803.86385.29276
9853.98983.192059944.21581.939699994.34180.2379910054.4980.2418310084.5782.41886
10114.6481.5039910134.6982.6959710144.7282.2033410174.8183.0287910194.9686.58719
10225.1788.7563810245.3188.7110810265.4686.3799810275.5386.0594310315.8286.31106
10325.8986.7095610346.0392.49017 10356.193.3155410366.1793.7284910376.2491.10829
10386.3290.2185910396.3994.1229210406.4693.25222 10426.695.61302 10443.295.87562
#Mann= 3 , 0 , 0
9523.335    0.04       09523.335    0.04       0 10443.2    0.04       0
#XS Ineff= 2 , 0
       09973.717        10063.99       0
Bank Sta=9523.335,10443.2
Exp/Cntr=0.3,0.1

Type RM Length L Ch R = 1 ,14494.64,95.838000,95.838000,95.838000
XS GIS Cut Line= 6
 776596.24836669856167.858146489776767.446332385856185.956587766
 776941.06900017856196.634796022777009.993804319 856209.37887305
777174.687294814856201.604106244 777373.75163331856206.172240029
#Sta/Elev= 30
9615.13792.210629623.93892.872619644.04990.683889664.16190.981749694.32889.67429
9704.38490.196179734.55189.232999754.66286.435799804.87686.208539824.91485.35204
9844.952 83.14669875.00882.756839915.08483.704179965.20882.362099985.394  69.133
9995.68467.0482110006.0163.6438610016.3665.3214610026.4371.9859310036.4876.27122
 10056.579.3348910106.5580.0784610126.5882.21857 10146.683.2892210156.61 86.2634
10186.6489.4360810256.66 89.713510296.6787.3705310346.6987.5738710395.47102.2913
#Mann= 3 , 0 , 0
9615.137   0.042       09615.137   0.042       010395.47   0.042       0
#XS Ineff= 2 , 0
       0                               0
Bank Sta=9615.137,10395.47
Exp/Cntr=0.3,0.1

Type RM Length L Ch R = 1 , 14398.8,69.545700,69.545700,69.545700
XS GIS Cut Line= 4
776690.207173645856273.089271635 776937.98732844856304.706423312
 777056.99910444856260.612132177 777396.06160447856261.132965505
#Sta/Elev= 30
9697.93589.446069712.84889.067859722.92985.416049783.41585.109699813.65982.31271
9843.90282.240819874.14583.801859894.30783.084549914.469 83.24239944.71381.60946
9965.86779.745659976.531 76.08569987.196 68.1533 9997.8664.5145110008.5269.39352
10029.8574.9563910051.1875.9640210062.0178.2691210112.6481.7121610132.6489.55212
10142.6490.9775810152.64 91.788610192.6492.0847710242.6490.3549910272.6488.84878
10332.6488.9614410352.6489.6179310392.64102.429810402.64104.9443 10413.7105.8368
#Mann= 3 , 0 , 0
9697.935  0.0505       09697.935  0.0505       0 10413.7  0.0505       0
#XS Ineff= 2 , 0
       0                               0
Bank Sta=9697.935,10413.7
Exp/Cntr=0.3,0.1

Type RM Length L Ch R = 1 ,14329.26,78.496300,78.496300,78.496300
XS GIS Cut Line= 4
776625.101701021856327.463072956776906.253517419856341.680080652
777094.485948652856347.105253011777413.521820068856343.202857554
#Sta/Elev= 30
9609.88186.226039629.80585.464059669.85685.558529689.88284.020229759.97184.31588
9769.98482.516889779.99781.717769870.11282.528369940.15981.431019960.16781.89207
9970.17178.1052910000.1862.2019410010.19 68.252510020.1976.04301 10030.281.72142
 10040.286.08428 10050.289.3783310090.2293.0922410100.2293.4535310120.2292.40367
10170.2292.3520110200.2390.6887310230.2390.4919910290.23 92.479110340.2493.25201
10350.2498.9232110360.24 103.69810370.24106.686110390.24109.586710398.76 110.072
#Mann= 3 , 0 , 0
9609.881   0.045       09609.881   0.045       010398.76   0.045       0
#XS Ineff= 2 , 0
       0                               0
Bank Sta=9609.881,10398.76
Exp/Cntr=0.3,0.1

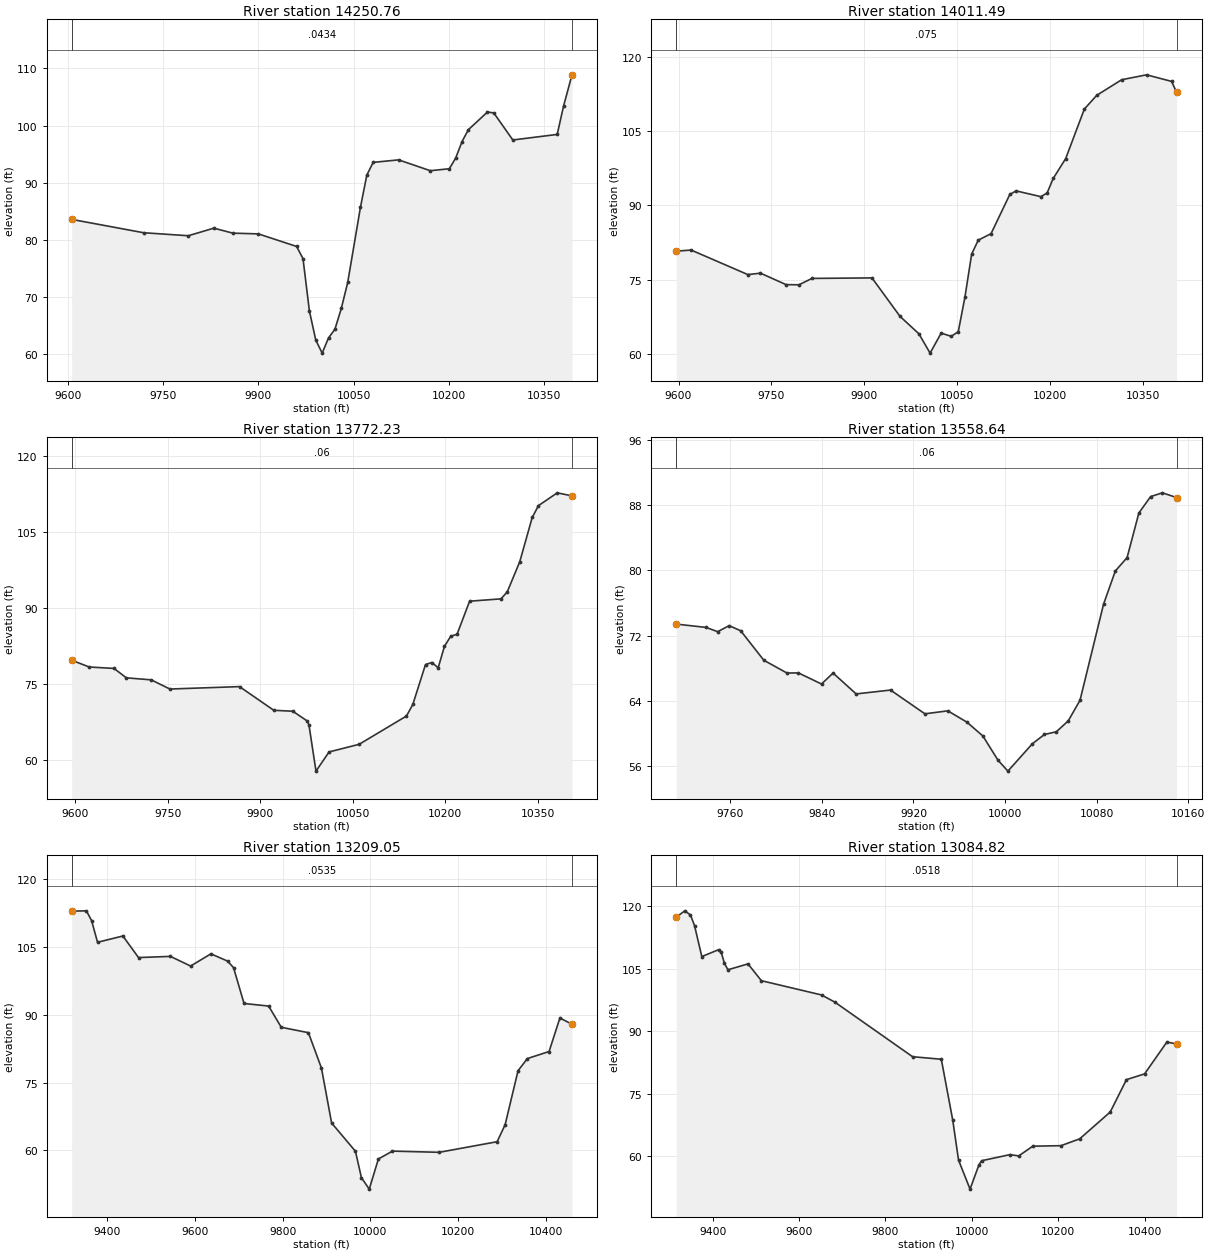
Type RM Length L Ch R = 1 ,14250.76,239.267200,239.267200,239.267200
XS GIS Cut Line= 6
776622.399887951856380.646538918776786.837636913 856401.04022416
776948.701752963 856415.27960784777109.856142575856432.732881531
777260.919487015856437.841989774777408.312644582856434.980564607
#Sta/Elev= 30
 9605.5583.574659719.01381.23832 9789.4880.712579829.63582.038019859.75181.16468
9899.90581.036359960.22178.834959970.29176.705539980.36267.542599990.43262.44581
 10000.560.1609210010.5762.8325210020.6464.3494410030.7167.9895610040.7872.53131
10060.8685.68223 10070.991.3235610080.9493.5559410121.0393.9947410171.0992.09646
10201.0992.44409 10211.194.32851 10221.197.21079 10231.199.28648 10261.1102.3656
10271.11102.218910301.11 97.476510371.1298.4489310381.13103.415610394.44108.8834
#Mann= 3 , 0 , 0
 9605.55  0.0434       0 9605.55  0.0434       010394.44  0.0434       0
#XS Ineff= 2 , 0
       0                               0
Bank Sta=9605.55,10394.44
Exp/Cntr=0.3,0.1

Type RM Length L Ch R = 1 ,14011.49,239.267200,239.267200,239.267200
XS GIS Cut Line= 6
776571.239184443856525.417817674776815.051726604856581.860382028
776993.653405551856677.376133984777046.662631282856695.242691629
777145.972762813856701.215955185777342.962417503 856682.12290577
#Sta/Elev= 30
9596.23780.731069620.30480.956119711.82675.997719732.23876.288059773.53473.97105
9794.27973.934529815.31175.225149912.143 75.32919957.42467.557999987.91964.03329
10005.9560.1316710023.8764.1765110040.1663.5198410051.4864.4816410062.2571.49908
10073.0380.1370110083.6682.9523310104.3584.2741910134.6192.1823110144.6992.91122
10184.76 91.744210194.7692.4747110204.7695.4412910224.8199.4413410254.89109.4334
10274.95112.220610315.13115.3677 10355.4116.356210395.68115.029910403.69 112.842
#Mann= 3 , 0 , 0
9596.237   0.075       09596.237   0.075       010403.69   0.075       0
#XS Ineff= 2 , 0
       0                               0
Bank Sta=9596.237,10403.69
Exp/Cntr=0.3,0.1

Type RM Length L Ch R = 1 ,13772.23,213.585200,213.585200,213.585200
XS GIS Cut Line= 6
776506.701427137856977.899514753776768.385558872856939.742830086
776839.174870467856904.374968854776886.019862219856835.241588926
 776946.38822023856795.827633056777248.611366503856732.603377342
#Sta/Elev= 30
9594.51779.687199622.947 78.34939663.13278.066059683.22576.205679723.48875.81018
9753.72173.997379866.52674.475769922.11369.800999952.91669.614079976.32367.68744
9979.13466.90392  9990.557.7879210011.6861.5750110060.4963.0854410137.1468.66861
10147.4370.9442510168.0278.8357610178.3179.2369310188.5878.1963210198.7682.44476
10208.9484.4260110219.1284.7992810239.48 91.342410290.3491.8031210300.4793.17538
10320.7499.12218   10341107.881310351.14110.215610381.54112.739910405.46112.1368
#Mann= 3 , 0 , 0
9594.517    0.06       09594.517    0.06       010405.46    0.06       0
#XS Ineff= 2 , 0
       0                               0
Bank Sta=9594.517,10405.46
Exp/Cntr=0.3,0.1

Type RM Length L Ch R = 1 ,13558.64,349.588800,349.588800,349.588800
XS GIS Cut Line= 6
776759.103773211857012.327438206776911.569116395856992.573728083
777011.650843467856986.698385183777057.323995925856968.694270599
777087.142540979856959.384284766777186.987109875856935.313639113
#Sta/Elev= 30
 9712.7173.405729738.82272.996729748.90672.474299758.98973.214779769.07372.58384
 9789.2468.973279809.40767.412149819.49167.419629839.65866.061439849.74267.40475
9869.88664.846569899.93865.320879929.98962.407859950.02462.773659966.70361.38359
9980.62359.691229993.84356.72382 10002.555.3845610023.9258.74656 10034.459.87501
10044.8760.21096 10055.261.5424810065.49 64.067710086.0675.8455710096.3579.91161
10106.6381.5598210116.9287.0234610127.2189.0353110137.4989.4925710149.8288.91618
#Mann= 3 , 0 , 0
 9712.71    0.06       0 9712.71    0.06       010149.82    0.06       0
#XS Ineff= 2 , 0
       0                               0
Bank Sta=9712.71,10149.82
Exp/Cntr=0.3,0.1

Type RM Length L Ch R = 1 ,13209.05,124.237400,124.237400,124.237400
XS GIS Cut Line= 6
776453.077104576857753.274335327776708.404721648857377.311815872
776799.163182304857299.095379599777010.606228942857204.972476996
777101.295557421857118.511581145777227.695182343856952.650209688
#Sta/Elev= 30
9318.663112.86219352.284112.93589364.175110.75379377.663105.98979435.521107.3749
9471.194102.61319543.999102.87359590.103100.7397 9636.38103.43569674.551101.8267
9688.098100.3724 9712.0192.470229768.13791.899119797.01387.210119858.91386.02214
9888.62878.213199911.85466.072479966.243 59.82689979.78754.013719997.73351.46416
10018.6458.1276310050.7859.8625810157.41 59.595410289.5861.9370810307.7765.67621
10337.3377.6220710358.7180.3071710408.1381.8581510432.8489.2711310460.4587.88022
#Mann= 3 , 0 , 0
9318.663  0.0535       09318.663  0.0535       010460.45  0.0535       0
#XS Ineff= 2 , 0
       0                               0
Bank Sta=9318.663,10460.45
Exp/Cntr=0.3,0.1

Type RM Length L Ch R = 1 ,13084.82,530.553400,530.553400,530.553400
XS GIS Cut Line= 6
776517.609704023857880.195672125776747.211263465857609.215738953
777000.485331007857320.644993426 777091.88870287857212.847584196
777192.542841361857082.274913672 777258.04571418856990.805163996
#Sta/Elev= 30
9315.813117.4158 9335.73118.94139348.837117.93679358.184115.39669375.051107.9652
9414.372109.6367 9420.06108.94849427.479106.30659435.529104.79849481.936106.2099
9512.874102.17759652.095 98.75479682.79997.043179862.79183.939029929.29183.32756
9955.81768.675499969.19159.12573 9995.7952.16545 10016.457.9949910022.4758.97946
10088.5660.4505910108.31 60.128910141.0162.4673610206.29 62.590810249.5564.23207
10320.1770.6637410357.7478.4360810399.7279.8161910451.2587.4525610473.6587.00259
#Mann= 3 , 0 , 0
9315.813  0.0518       09315.813  0.0518       010473.65  0.0518       0
#XS Ineff= 2 , 0
       0                               0
Bank Sta=9315.813,10473.65
Exp/Cntr=0.3,0.1

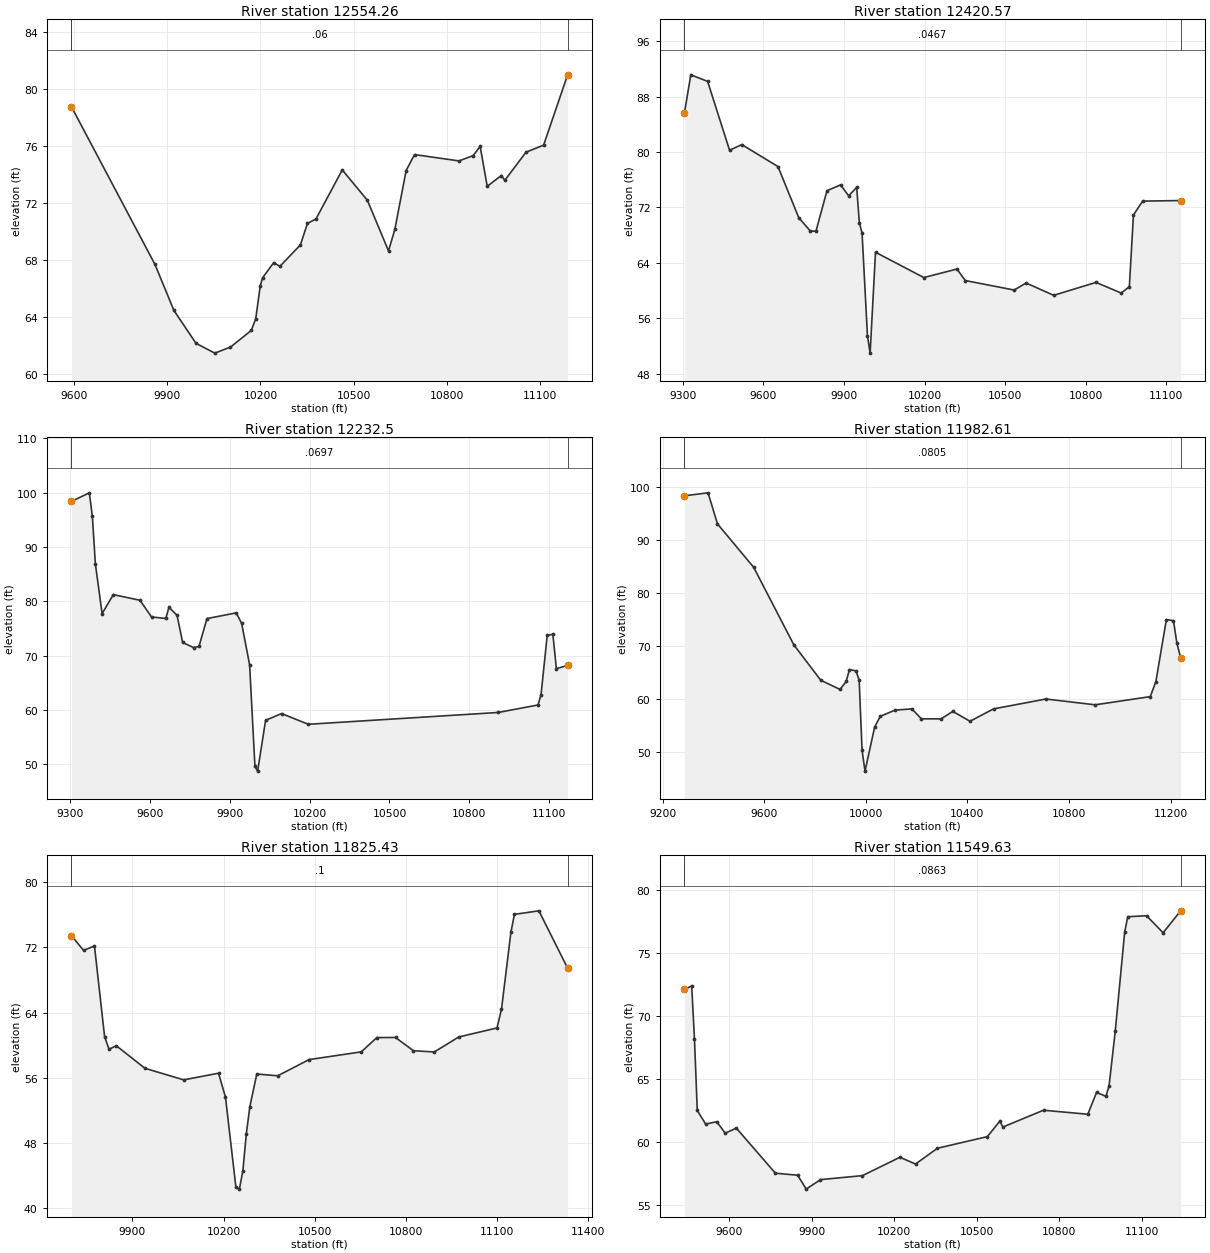
Type RM Length L Ch R = 1 ,12554.26,133.692200,133.692200,133.692200
XS GIS Cut Line= 6
777012.915173978857495.648121208777252.207131982857550.301222742
777385.147108674857575.412107214777571.263076067 857602.00010255
777682.046389997857495.648121208 778453.09825477857082.057082608
#Sta/Elev= 30
9591.78978.774259860.43867.725449921.49964.495159992.58862.18683 10053.261.49758
 10103.761.9187310170.6563.0876610185.0963.9125310199.5366.2142310207.3166.78939
10242.8567.8423710262.7567.5826310328.8169.08905 10351.570.5923810378.9570.90882
10463.5774.3479410544.4272.21754 10612.568.6652110632.8170.1728110669.2474.30487
10696.2875.4232210839.4674.9782610884.8575.3511710907.5575.9949710930.24 73.1956
10975.6373.9518410986.98   73.6211055.0775.5900611111.8176.0864711189.0881.01629
#Mann= 3 , 0 , 0
9591.789    0.06       09591.789    0.06       011189.08    0.06       0
#XS Ineff= 2 , 0
       0                10071.33       0
Bank Sta=9591.789,11189.08
Exp/Cntr=0.3,0.1

Type RM Length L Ch R = 1 ,12420.57,188.067800,188.067800,188.067800
XS GIS Cut Line= 6
776777.535297394857946.268738344777213.702476323857727.970601082
777301.037298262857710.741539791777614.746036828 857709.79923223
777828.862553805857653.123150751778478.751421034 857312.73323518
#Sta/Elev= 30
9305.94185.666079329.49391.152769392.19290.207089473.87780.256619519.346 81.0762
9654.275  77.8949731.57770.513119774.26868.607519795.56768.54156  9836.8 74.4175
9887.36175.252179917.36873.673369947.38674.889649957.39569.742359967.40368.30798
9987.41953.479419997.42850.9441910017.4465.5179510197.45  61.864 10320.763.09281
10351.8461.43165 10533.860.0581110578.3861.0745710681.1859.2960510838.7261.16429
10932.48 59.625310962.8760.5465710978.1770.9130911012.4372.9078611153.7972.98979
#Mann= 3 , 0 , 0
9305.941  0.0467       09305.941  0.0467       011153.79  0.0467       0
#XS Ineff= 2 , 0
       0                10043.83       0
Bank Sta=9305.941,11153.79
Exp/Cntr=0.3,0.1

Type RM Length L Ch R = 1 , 12232.5,249.894300,249.894300,249.894300
XS GIS Cut Line= 6
776725.771212935858082.513159841777098.601338804857910.676597655
777550.811463416857899.275342867777676.270460933857868.983270809
777857.337487221857792.283996657778441.614576727857457.409823939
#Sta/Elev= 30
9304.475 98.36889371.65199.943589382.993 95.63829394.33486.84736 9419.6577.72212
9461.80281.21306 9561.8680.17731 9605.4777.09772 9659.1976.828589670.88178.88355
9701.39877.396849722.30572.413329763.27871.473759783.72471.666439813.96776.80509
9924.09377.855959944.12875.931599974.18268.297829994.21749.5897710004.2348.73315
10034.2758.0811710094.3459.3258610194.7957.3527110908.4759.5271511058.3160.90333
11069.8362.8243611092.8873.6997211114.1873.9137511127.4667.5885411169.6668.18719
#Mann= 3 , 0 , 0
9304.475  0.0697       09304.475  0.0697       011169.66  0.0697       0
#XS Ineff= 2 , 0
       0                10106.98       0
Bank Sta=9304.475,11169.66
Exp/Cntr=0.3,0.1

Type RM Length L Ch R = 1 ,11982.61,157.175100,157.175100,157.175100
XS GIS Cut Line= 6
776830.032045007858588.608182251777053.296837926858421.002176926
777229.432042807858274.624373287 777325.31392473858181.262536705
777395.002555311858086.729769722778439.515667766857507.783638701
#Sta/Elev= 30
 9285.2198.366279378.10898.922139415.28393.055079557.84784.870739716.226 70.2239
9822.34563.55101 9898.0561.819659922.14163.321949935.28765.571189960.69665.31566
9973.35863.622639984.94450.34407 9996.5346.4028810034.45 54.730410056.8156.74581
10113.9457.9068310181.1958.15138 10218.556.2746910296.2656.2645310342.2957.67393
10410.0355.8132210502.8158.1473910709.4860.0132310903.0358.91753 11120.360.46239
11142.4663.31291 11183.775.0030211211.7874.7879511224.9370.6170911239.8167.81411
#Mann= 3 , 0 , 0
 9285.21  0.0805       0 9285.21  0.0805       011239.81  0.0805       0
#XS Ineff= 2 , 0
       09941.627        10273.78       0
Bank Sta=9285.21,11239.81
Exp/Cntr=0.3,0.1

Type RM Length L Ch R = 1 ,11825.43,275.805100,275.805100,275.805100
XS GIS Cut Line= 4
777341.744598877858384.783775449777491.242000383858286.628915846
777526.087687862858109.830502287778637.846516561857488.893458173
#Sta/Elev= 30
9699.557 73.4467 9739.3471.631949775.22872.174629808.48561.04517 9823.0859.47844
9847.00559.916549941.21257.1450810068.81 55.721610183.3556.5384110206.2553.60305
10240.6242.5149110252.0742.2942110263.5244.5564410274.9849.1273810286.4352.42926
10309.3456.4406710378.0656.2212710481.1558.2120810652.9659.1614410704.2560.91748
10765.7760.9284210824.7759.2968210893.4959.1530110973.6760.9898211099.6762.10276
 11114.464.3887511145.4873.8667711156.9476.0606611237.4576.4947111332.0169.44794
#Mann= 3 , 0 , 0
9699.557     0.1       09699.557     0.1       011332.01     0.1       0
#XS Ineff= 2 , 0
       09961.942        10267.23       0
Bank Sta=9699.557,11332.01
Exp/Cntr=0.3,0.1

Type RM Length L Ch R = 1 ,11549.63,355.430600,355.430600,355.430600
XS GIS Cut Line= 4
   777379.108199858406.396170303777735.145792037858343.450297505
777798.091664791858119.205625638778864.237385333857544.824536353
#Sta/Elev= 30
9436.675 72.12839462.96872.399069473.123 68.17679483.27862.516969513.74361.44032
9554.36461.625449584.82960.716059625.44961.11597 9767.6257.539459848.55757.38067
9879.71656.276119931.64957.0293610084.4357.3487510220.74 58.805310277.5358.26711
10357.0459.5193510538.7860.4430910584.2261.6649110595.5861.2047610743.2462.53958
10904.4662.2186910936.3563.9483510970.4263.6419410981.7864.47143 11004.568.84006
11038.5876.6641611049.9377.8947311118.0977.9756811178.5576.6215311242.1778.36312
#Mann= 3 , 0 , 0
9436.675  0.0863       09436.675  0.0863       011242.17  0.0863       0
#XS Ineff= 2 , 0
       0 9872.07        10188.65       0
Bank Sta=9436.675,11242.17
Exp/Cntr=0.3,0.1