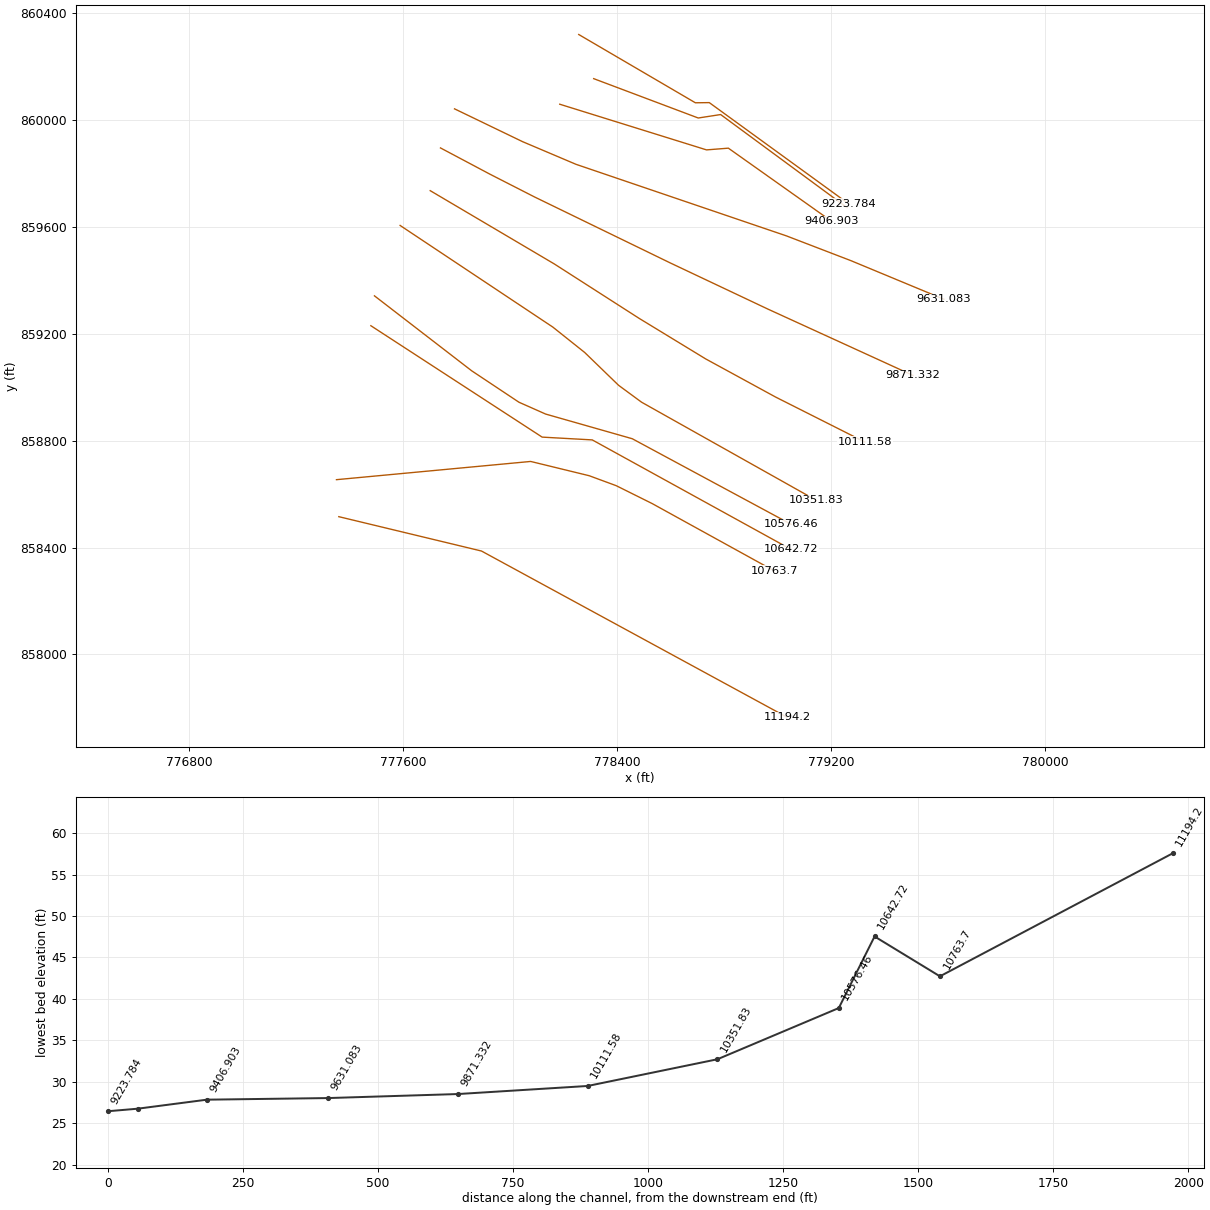
HEC-RAS study 16031_ras.prj: 16031

--- 16031_ras.g01 (geometry) --- (continued)

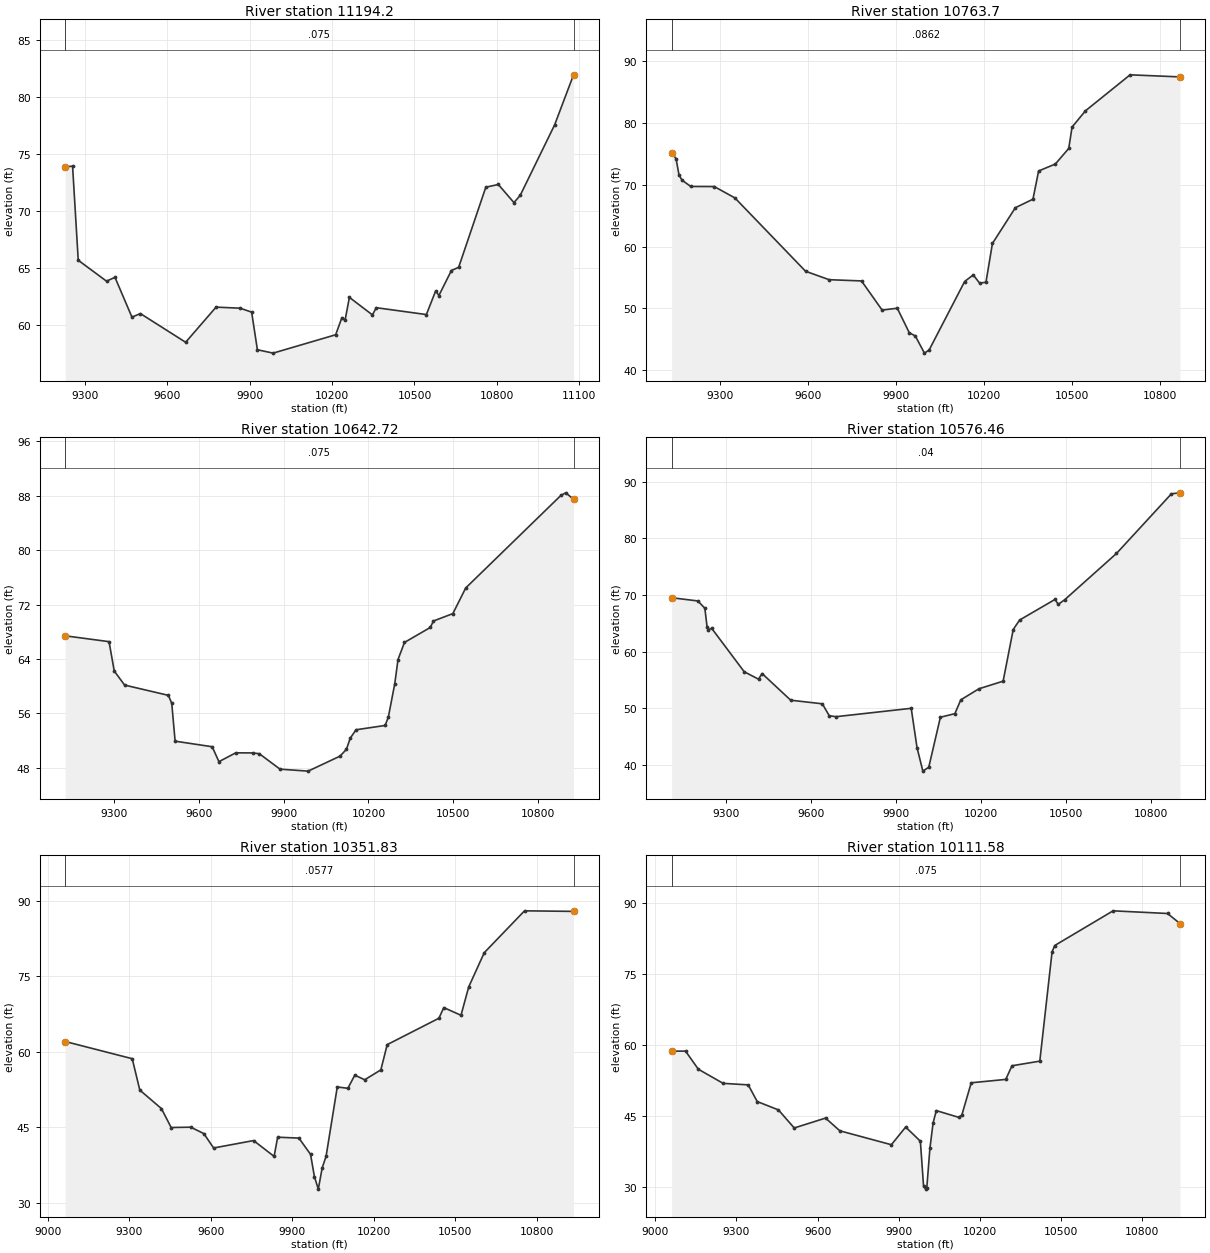
Type RM Length L Ch R = 1 , 11194.2,430.492500,430.492500,430.492500
XS GIS Cut Line= 3
777358.891783927 858515.37909838777892.609769826858386.877663503
779035.470772867857765.287169615
#Sta/Elev= 30
9228.894 73.86879255.74973.92707 9276.3265.684729379.178  63.8559410.03564.18824
 9471.7560.702469502.60761.012939667.17958.498649777.86461.578329865.51261.48448
9907.37161.139719928.30157.844389985.48657.5477610213.1559.1568710235.92 60.6616
 10247.360.4266910263.1762.4310410346.8960.8990510361.14 61.527810543.2760.92731
10577.1262.9984810588.8162.5954110634.3464.7831410660.8465.0708410759.5672.08423
10805.0972.3244110862.0170.7355810884.7771.3697311009.9977.5434111078.8381.93217
#Mann= 3 , 0 , 0
9228.894   0.075       09228.894   0.075       011078.83   0.075       0
#XS Ineff= 2 , 0
       09875.451        10072.96       0
Bank Sta=9228.894,11078.83
Exp/Cntr=0.3,0.1

Type RM Length L Ch R = 1 , 10763.7,120.981000,120.981000,120.981000
XS GIS Cut Line= 6
777350.181924194858653.787923887778076.566505462858721.934335291
778295.590516925858668.519131765778396.738042086858631.198642612
778530.871663153858564.484384134778987.396847397858312.821061388
#Sta/Elev= 30
 9133.6875.189389148.56374.256619158.607 71.6371 9168.6570.775599198.78269.74034
9279.13469.724179349.44167.883649590.49555.997979670.84654.630369781.32954.43059
9851.63649.703979903.30350.009059944.28746.033889964.77645.516519996.00242.72846
10011.8543.2248810133.1454.3365810162.4755.4043510184.0454.0866710205.8354.21171
10227.9560.5030710306.1466.2986510366.1867.67696 10385.572.25187 10442.673.38012
10488.2775.9067710499.6979.3724610545.3782.00787 10697.687.8364710867.8387.50008
#Mann= 3 , 0 , 0
 9133.68  0.0862       0 9133.68  0.0862       010867.83  0.0862       0
#XS Ineff= 2 , 0
       09904.547                       0
Bank Sta=9133.68,10867.83
Exp/Cntr=0.3,0.1

Type RM Length L Ch R = 1 ,10642.72,66.261700,66.261700,66.261700
XS GIS Cut Line= 4
777478.878283262859229.622168958778119.503283262858812.955502301
778307.003283262 858802.53883563779049.190783262858393.684668943
#Sta/Elev= 30
9126.53967.402129281.74466.544529300.08562.235019336.76760.168679491.71458.66132
9503.64357.505269515.57251.931899646.79251.11424 9670.6548.920579730.29550.21942
9789.94150.205589813.632 50.08869886.99547.820739986.38947.5324110099.0849.72915
10121.9250.7288910135.6152.3854710156.1753.6074610258.9254.2382510270.3455.45754
10293.1760.3814410304.5963.9167210327.4266.4269410418.7668.6280310430.1769.57919
10498.6770.6621710544.34 74.433410881.7188.0409810898.2788.3990210925.8987.45859
#Mann= 3 , 0 , 0
9126.539   0.075       09126.539   0.075       010925.89   0.075       0
#XS Ineff= 2 , 0
       09910.108                       0
Bank Sta=9126.539,10925.89
Exp/Cntr=0.3,0.1

Type RM Length L Ch R = 1 ,10576.46,224.631300,224.631300,224.631300
XS GIS Cut Line= 6
777492.261657152859341.411011721777856.097390289859060.926924474
778032.799319258 858943.45677732778132.567419502858899.196515839
778456.646882386858806.915502228779051.401566308858486.496163328
#Sta/Elev= 30
9108.76869.512349201.16368.945029225.86567.658379233.92164.302439238.492 63.8864
9250.29964.090439364.75756.450559415.26355.13568 9427.8956.132149528.90251.42481
9640.54450.788229665.119 48.67259689.27648.515259954.33749.991099974.82643.05765
9995.41238.9023210016.26 39.588610057.3248.41598 10108.549.0467410129.4151.48787
10193.2853.4381110278.79 54.785110314.3963.8958510336.9165.5749810461.8969.21457
10473.3168.3441110496.1569.1596610678.85 77.326910872.9787.8661610903.1288.03229
#Mann= 3 , 0 , 0
9108.768    0.04       09108.768    0.04       010903.12    0.04       0
#XS Ineff= 2 , 0
       09914.933                       0
Bank Sta=9108.768,10903.12
Exp/Cntr=0.3,0.1

Type RM Length L Ch R = 1 ,10351.83,240.249200,240.249200,240.249200
XS GIS Cut Line= 6
777588.230177902859604.688354914778159.617596668859224.422730593
778278.669556189859129.535854516778405.429253274859006.777360743
778491.345107109 858943.61722303779143.902518314858577.055705177
#Sta/Elev= 30
9064.73862.03549 9311.4158.61879 9339.2452.388299418.77948.720819454.56844.96048
 9526.7745.02448 9575.0143.74815 9610.8140.892269757.92642.366979833.42539.22555
9846.47243.036599924.70742.858289967.49539.635069981.80835.192949996.12132.72678
10010.42 36.963810024.6739.2329210065.88 53.0099 10104.952.7454610130.2955.35312
10166.7754.4385110226.1756.3983510249.6561.4148610439.9166.6557710457.7968.76956
10521.1467.2427410549.5272.8705310606.6879.66624 10754.987.9786110935.2587.86754
#Mann= 3 , 0 , 0
9064.738  0.0577       09064.738  0.0577       010935.25  0.0577       0
#XS Ineff= 2 , 0
       09843.564                       0
Bank Sta=9064.738,10935.25
Exp/Cntr=0.3,0.1

Type RM Length L Ch R = 1 ,10111.58,240.249300,240.249300,240.249300
XS GIS Cut Line= 6
777700.811568812 859734.86447293778165.165111466859460.604395829
778481.879066779 859257.42847362778731.434108212859105.379133659
778992.333690718858963.035142141779326.222714792858794.796483468
#Sta/Elev= 30
9060.52658.70501 9111.7458.725569159.16454.881859250.821 51.89369343.54151.57506
9376.75848.040699455.19346.272729513.51842.451189629.22644.543689682.23541.84721
 9872.5438.905119925.492  42.6479979.80139.647759991.58230.139259999.63429.50548
10003.3629.6510610015.1138.1744410026.87 43.530410038.6346.1258610120.92  44.714
10132.7545.13231 10167.852.0170410295.4152.7298810318.3655.6178310421.2656.59854
10466.5979.7243410476.4581.0735310692.15 88.414510893.4587.8499710939.4785.71953
#Mann= 3 , 0 , 0
9060.526   0.075       09060.526   0.075       010939.47   0.075       0
#XS Ineff= 2 , 0
       09725.241                       0
Bank Sta=9060.526,10939.47
Exp/Cntr=0.3,0.1

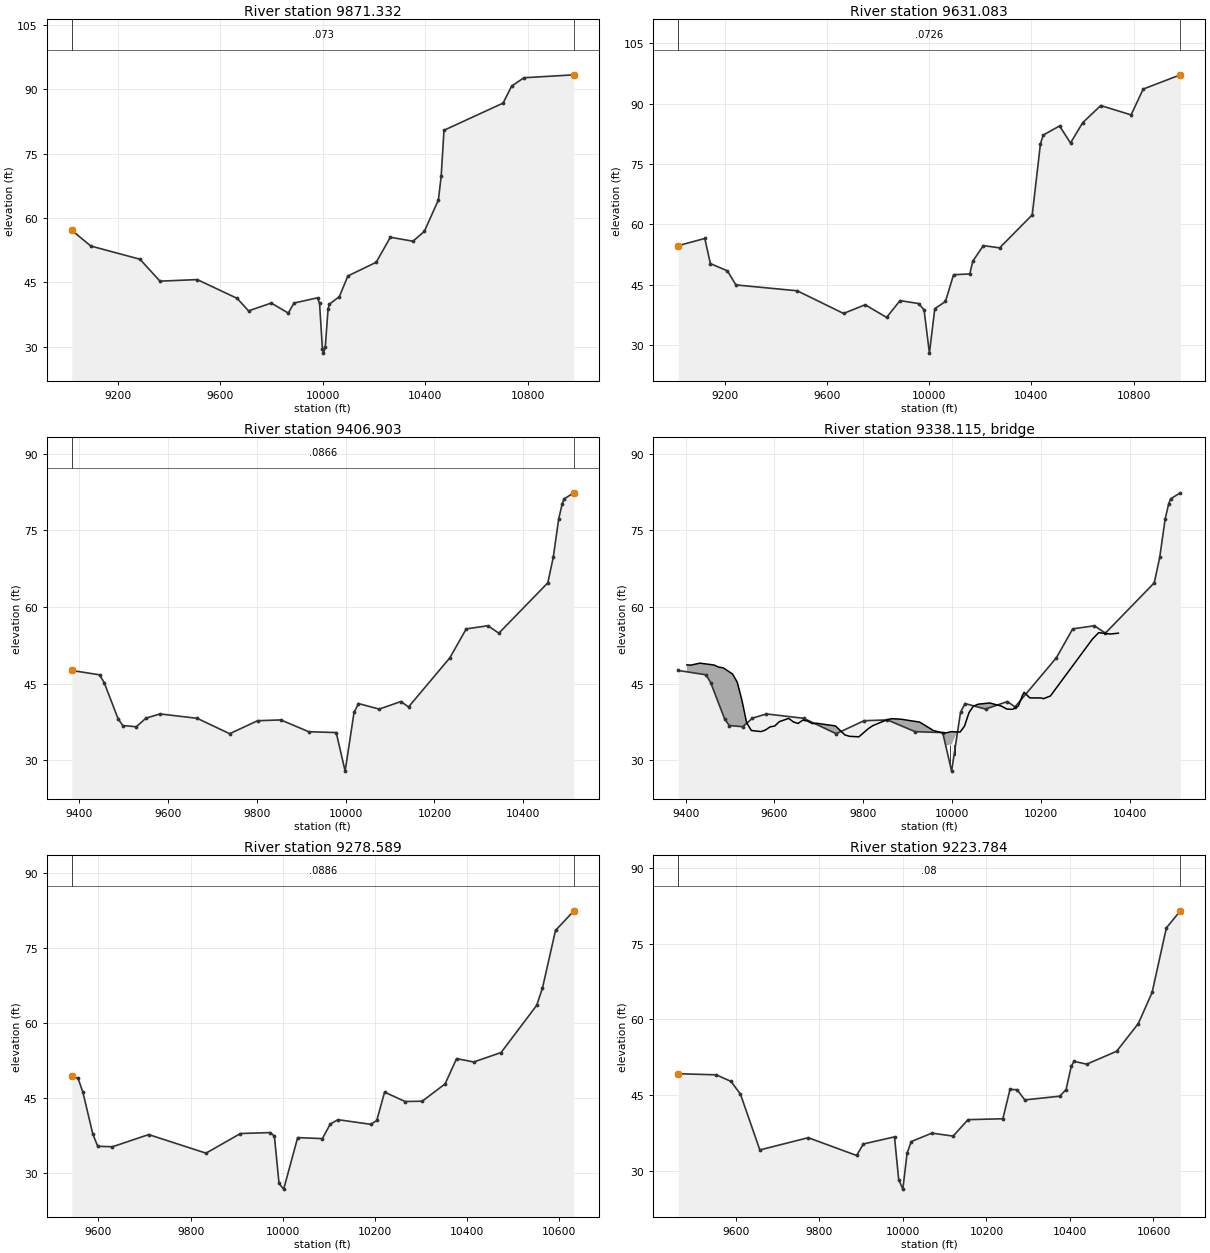
Type RM Length L Ch R = 1 ,9871.332,240.249200,240.249200,240.249200
XS GIS Cut Line= 6
777739.231063845859894.685609999777923.828893068859796.665453881
778090.398916695859711.588025181778600.004349955859463.895485567
778963.821020136859291.892142283779506.395263793 859043.78856071
#Sta/Elev= 30
9019.14957.151859093.61553.486439285.61650.409949363.72645.305729509.51945.66463
9665.34141.294129709.75738.38195 9798.59 40.19959865.215 37.86499887.42340.19963
9979.27241.419339987.35140.116379998.43729.4956310002.4428.53229 10009.529.86776
10020.5638.8168410025.8539.93984 10064.841.7121910097.9846.5137110208.5849.70015
10263.8855.5375210352.3654.6069210396.5356.8882510451.5164.1976510462.5169.75741
 10473.580.4621110704.4286.7910810737.4790.7168310785.56 92.694810980.85  93.377
#Mann= 3 , 0 , 0
9019.149   0.073       09019.149   0.073       010980.85   0.073       0
#XS Ineff= 2 , 0
       09657.073                       0
Bank Sta=9019.149,10980.85
Exp/Cntr=0.3,0.1

Type RM Length L Ch R = 1 ,9631.083,224.180000,224.180000,224.180000
XS GIS Cut Line= 6
777791.767659477860040.887022584778046.390964033 859918.07730776
778246.242025115859833.329582899779033.073955251859565.732099876
779274.821291861859472.872272546779622.726196926859328.461624949
#Sta/Elev= 30
9016.637 54.74829120.68956.516829142.50550.286549209.44648.468559242.58244.98321
9482.70943.527159664.26437.894349748.689  40.0589832.84436.916199885.44241.09602
9958.751 40.35099979.66638.7678610000.58 28.048310021.5339.0756310063.4540.87882
10095.0847.5110110158.7547.7167810170.4650.86859 10211.854.7537110275.4754.18255
10403.3262.3781110435.4680.0013510446.1782.1843210510.4584.45868 10553.380.21371
10600.7385.2529110671.6889.5234610790.5187.2082110837.9493.6153210983.3697.15156
#Mann= 3 , 0 , 0
9016.637  0.0726       09016.637  0.0726       010983.36  0.0726       0
#XS Ineff= 2 , 0
       09598.128                       0
Bank Sta=9016.637,10983.36
Exp/Cntr=0.3,0.1

Type RM Length L Ch R = 1 ,9406.903,128.314000,128.314000,128.314000
XS GIS Cut Line= 4
778185.345277698860058.179686049778734.387381435859887.342710549
778816.045306862859893.789388859779202.846006126859619.805560195
#Sta/Elev= 30
9383.19347.559129445.66846.709689456.141 45.1951 9487.5638.098819498.03336.77557
9528.52836.544559550.397 38.22649581.81639.050699665.59938.19706 9738.9135.17565
9801.74737.723579854.11237.878439916.94935.570989978.87635.403269998.93827.85426
   1001939.3322510029.0341.0836810075.5939.9994510124.5241.4741510141.8240.42787
 10234.950.0423610271.6755.6950410320.6856.3185210345.1954.8589610455.4864.71837
10467.7469.7104810479.9977.2187510487.83 80.157310492.2581.1590710514.1282.33577
#Mann= 3 , 0 , 0
9383.193  0.0866       09383.193  0.0866       010514.12  0.0866       0
#XS Ineff= 2 , 0
       0                               0
Bank Sta=9383.193,10514.12
Exp/Cntr=0.3,0.1

Type RM Length L Ch R = 3 ,9338.115,,,
BEGIN DESCRIPTION:
END DESCRIPTION:
Bridge Culvert--1,0,-1,-1, 0
Deck Dist Width WeirC Skew NumUp NumDn MinLoCord MaxHiCord MaxSubmerge Is_Ogee
43.657000,41.000000,2.6,0, 60, 60, , , 0.95, 0, 0,0,,
 9402.78 9411.15 9432.15 9463.64 9474.14 9484.64 9505.65 9516.19 9526.72 9537.26
 9547.79 9569.62 9579.40 9589.93 9600.47 9611.00 9632.07 9642.61 9653.14 9663.68
 9674.21 9684.75 9695.28 9737.42 9758.49 9769.03 9790.10 9811.17 9821.70 9853.31
 9863.84 9884.91 9927.05 9958.03 9978.05 9987.35 9987.35 9998.0610012.6510012.65
10018.0710028.0710038.0810048.0910058.8610084.7110110.5710123.4910136.4210149.35
10158.4010162.2710175.2010201.0510205.7410221.5310316.2110330.3110356.1710374.62
   48.66   48.60   48.99   48.63   48.23   48.07   46.86   45.24   41.70   37.34
   35.81   35.59   35.89   36.51   36.68   37.54   38.18   37.48   37.19   37.83
   37.67   37.18   37.22   36.70   34.95   34.67   34.57   36.16   36.77   37.91
   38.12   38.02   37.45   35.80   35.36   35.36   35.36   35.58   35.52   35.52
   35.50   36.67   39.30   40.58   40.96   41.20   40.60   40.00   39.95   40.61
   42.67   43.29   42.19   42.18   42.03   42.57   53.71   54.96   54.69   54.86
 -951.34 -951.40 -951.01 -951.37 -951.77 -951.93 -953.14 -954.76 -958.30 -962.66
 -964.19 -964.41 -964.11 -963.49 -963.32 -962.46 -961.82 -962.52 -962.81 -962.17
 -962.33 -962.82 -962.78 -963.30 -965.05 -965.33 -965.43 -963.84 -963.23 -962.09
 -961.88 -961.98 -962.55 -964.20 -964.64 -964.64   32.86   33.08   33.02 -964.48
 -964.50 -963.33 -960.70 -959.42 -959.04 -958.80 -959.40 -960.00 -960.05 -959.39
 -957.33 -956.71 -957.81 -957.82 -957.97 -957.43 -946.29 -945.04 -945.31 -945.14
 9402.78 9411.15 9432.15 9463.64 9474.14 9484.64 9505.65 9516.19 9526.72 9537.26
 9547.79 9569.62 9579.40 9589.93 9600.47 9611.00 9632.07 9642.61 9653.14 9663.68
 9674.21 9684.75 9695.28 9737.42 9758.49 9769.03 9790.10 9811.17 9821.70 9853.31
 9863.84 9884.91 9927.05 9958.03 9978.05 9987.35 9987.35 9998.0610012.6510012.65
10018.0710028.0710038.0810048.0910058.8610084.7110110.5710123.4910136.4210149.35
10158.4010162.2710175.2010201.0510205.7410221.5310316.2110330.3110356.1710374.62
   48.66   48.60   48.99   48.63   48.23   48.07   46.86   45.24   41.70   37.34
   35.81   35.59   35.89   36.51   36.68   37.54   38.18   37.48   37.19   37.83
   37.67   37.18   37.22   36.70   34.95   34.67   34.57   36.16   36.77   37.91
   38.12   38.02   37.45   35.80   35.36   35.36   35.36   35.58   35.52   35.52
   35.50   36.67   39.30   40.58   40.96   41.20   40.60   40.00   39.95   40.61
   42.67   43.29   42.19   42.18   42.03   42.57   53.71   54.96   54.69   54.86
 -951.34 -951.40 -951.01 -951.37 -951.77 -951.93 -953.14 -954.76 -958.30 -962.66
 -964.19 -964.41 -964.11 -963.49 -963.32 -962.46 -961.82 -962.52 -962.81 -962.17
 -962.33 -962.82 -962.78 -963.30 -965.05 -965.33 -965.43 -963.84 -963.23 -962.09
 -961.88 -961.98 -962.55 -964.20 -964.64 -964.64   32.86   33.08   33.02 -964.48
 -964.50 -963.33 -960.70 -959.42 -959.04 -958.80 -959.40 -960.00 -960.05 -959.39
 -957.33 -956.71 -957.81 -957.82 -957.97 -957.43 -946.29 -945.04 -945.31 -945.14
Pier Skew, UpSta & Num, DnSta & Num=  ,9995.45, 2 ,9995.45, 2 , 0 , 0 , 0 ,,
    2.00    2.00
 -964.47   35.53
    2.00    2.00
 -964.47   35.53
Pier Skew, UpSta & Num, DnSta & Num=  ,10004.55, 2 ,10004.55, 2 , 0 , 0 , 0 ,,
    2.00    2.00
 -964.45   35.55
    2.00    2.00
 -964.45   35.55
BR Coef=-1 , 0 , 0 ,, 0 ,,,0.8,0,1,0,
WSPro=,,,, 1 ,,,, 0 ,,,, 0 ,,,,-1 ,-1 ,-1 , 0 , 0 , 0 , 0 , 0
BC Design=,, 0 ,, 0 ,,,,,,

Type RM Length L Ch R = 1 ,9278.589,54.804900,54.804900,54.804900
XS GIS Cut Line= 4
778312.296256423 860153.81848748778703.394741267860006.619332463
778787.201559484860019.512689114779259.957969695859671.392059743
#Sta/Elev= 30
9542.14149.297229555.71548.93674  9566.446.113779587.76937.803349598.45435.33714
9630.509 35.2402 9709.1237.676019833.52133.958369908.31437.888459971.76538.07231
9981.88337.42234    999227.9099310002.1226.7648310032.4737.0733110086.1636.86465
10103.0239.7621610119.8940.6558910191.1139.7271510204.2140.5050210221.0846.17148
10265.6244.2910310302.8744.3498710352.5547.8214610377.3952.8744310414.6452.19275
10474.0554.0914910551.2563.5202610563.6766.92894 10592.178.4968910631.9282.42861
#Mann= 3 , 0 , 0
9542.141  0.0886       09542.141  0.0886       010631.92  0.0886       0
#XS Ineff= 2 , 0
       0                               0
Bank Sta=9542.141,10631.92
Exp/Cntr=0.3,0.1

Type RM Length L Ch R = 1 ,9223.784,102.955800,102.955800,102.955800
XS GIS Cut Line= 4
778256.350772381860318.926805705778692.650277406860063.564990968
778744.685728818 860064.16358076779266.404648036859685.359862775
#Sta/Elev= 30
9461.968 49.27199553.099 49.05579588.52347.741919611.03345.221229657.38134.20466
 9773.2536.627069889.11933.111819905.27335.385349979.85536.789949989.85628.36273
9999.857 26.459810009.8633.5218610019.9335.8617810069.3637.5309210120.2436.94177
10155.8740.1918110239.3840.37203 10256.4 46.171610273.42 46.117710291.8144.09953
10375.55 44.831210390.6746.1397310403.0350.7053510409.5951.72594 10440.151.16205
10511.7153.7058310563.6859.1860410596.8165.3582210630.85  78.09710664.2881.47512
#Mann= 3 , 0 , 0
9461.968    0.08       09461.968    0.08       010664.28    0.08       0
#XS Ineff= 2 , 0
       0 9561.05                       0
Bank Sta=9461.968,10664.28
Exp/Cntr=0.3,0.1