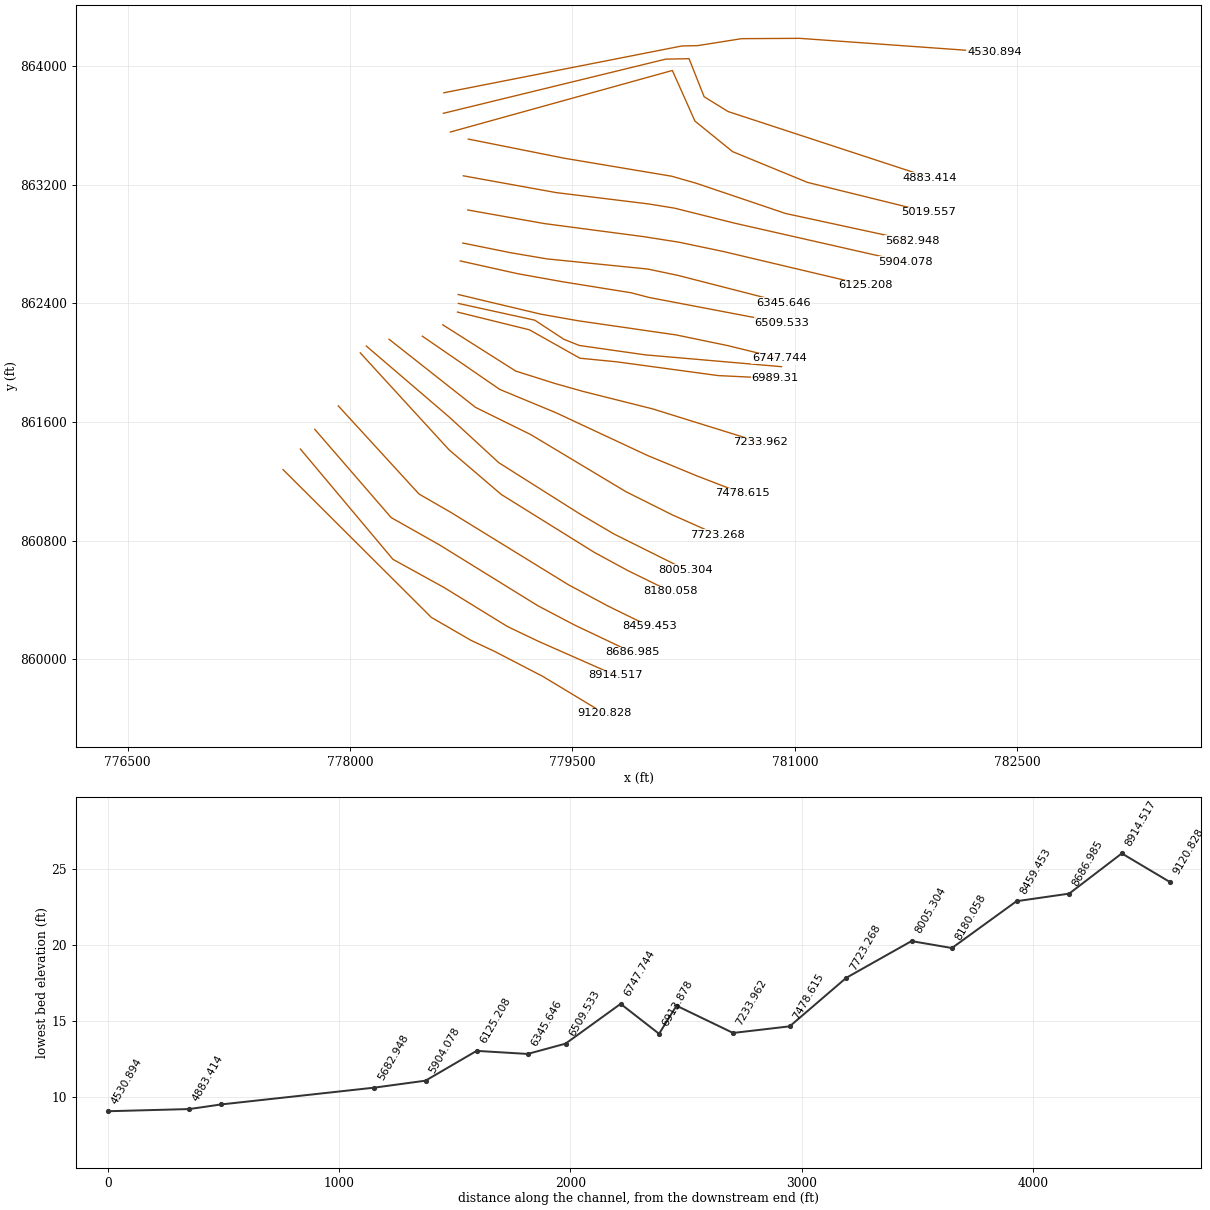
HEC-RAS study 16031_ras.prj: 16031

--- 16031_ras.g01 (geometry) --- (continued)

Type RM Length L Ch R = 3 ,9181.627,,,
BEGIN DESCRIPTION:
END DESCRIPTION:
Bridge Culvert--1,0,-1,-1, 0
Deck Dist Width WeirC Skew NumUp NumDn MinLoCord MaxHiCord MaxSubmerge Is_Ogee
34.477900,34.000000,2.6,0, 37, 37, , , 0.95, 0, 0,0,,
 9510.12 9529.01 9553.41 9577.80 9590.00 9602.20 9614.40 9626.59 9638.79 9650.99
 9663.19 9675.39 9686.18 9711.98 9724.18 9738.56 9748.58 9760.77 9772.97 9790.95
 9834.25 9858.93 9883.61 9908.30 9920.64 9984.60 9984.6010015.4010015.4010044.06
10068.7410129.7410153.6310176.7610212.0210223.7710241.92
   34.35   34.38   34.28   34.33   34.18   34.25   34.16   33.96   33.98   33.76
   33.92   33.79   33.58   33.62   33.55   33.13   33.19   33.06   33.14   32.95
   32.74   32.79   32.71   32.72   32.87   34.52   34.52   35.40   35.40   35.98
   36.61   37.39   37.99   38.45   39.61   40.09   40.60
 -965.65 -965.62 -965.72 -965.67 -965.82 -965.75 -965.84 -966.04 -966.02 -966.24
 -966.08 -966.21 -966.42 -966.38 -966.45 -966.87 -966.81 -966.94 -966.86 -967.05
 -967.26 -967.21 -967.29 -967.28 -967.13 -965.48   32.02   32.90 -964.60 -964.02
 -963.39 -962.61 -962.01 -961.55 -960.39 -959.91 -959.40
 9510.12 9529.01 9553.41 9577.80 9590.00 9602.20 9614.40 9626.59 9638.79 9650.99
 9663.19 9675.39 9686.18 9711.98 9724.18 9738.56 9748.58 9760.77 9772.97 9790.95
 9834.25 9858.93 9883.61 9908.30 9920.64 9984.60 9984.6010015.4010015.4010044.06
10068.7410129.7410153.6310176.7610212.0210223.7710241.92
   34.35   34.38   34.28   34.33   34.18   34.25   34.16   33.96   33.98   33.76
   33.92   33.79   33.58   33.62   33.55   33.13   33.19   33.06   33.14   32.95
   32.74   32.79   32.71   32.72   32.87   34.52   34.52   35.40   35.40   35.98
   36.61   37.39   37.99   38.45   39.61   40.09   40.60
 -965.65 -965.62 -965.72 -965.67 -965.82 -965.75 -965.84 -966.04 -966.02 -966.24
 -966.08 -966.21 -966.42 -966.38 -966.45 -966.87 -966.81 -966.94 -966.86 -967.05
 -967.26 -967.21 -967.29 -967.28 -967.13 -965.48   32.02   32.90 -964.60 -964.02
 -963.39 -962.61 -962.01 -961.55 -960.39 -959.91 -959.40
Pier Skew, UpSta & Num, DnSta & Num=  ,9994.53, 2 ,9994.53, 2 , 0 , 0 , 0 ,,
    2.00    2.00
 -965.16   34.84
    2.00    2.00
 -965.16   34.84
Pier Skew, UpSta & Num, DnSta & Num=  ,10005.47, 2 ,10005.47, 2 , 0 , 0 , 0 ,,
    2.00    2.00
 -964.85   35.15
    2.00    2.00
 -964.85   35.15
BR Coef=-1 , 0 , 0 ,, 0 ,,,0.8,0,1,0,
WSPro=,,,, 1 ,,,, 0 ,,,, 0 ,,,,-1 ,-1 ,-1 , 0 , 0 , 0 , 0 , 0
BC Design=,, 0 ,, 0 ,,,,,,

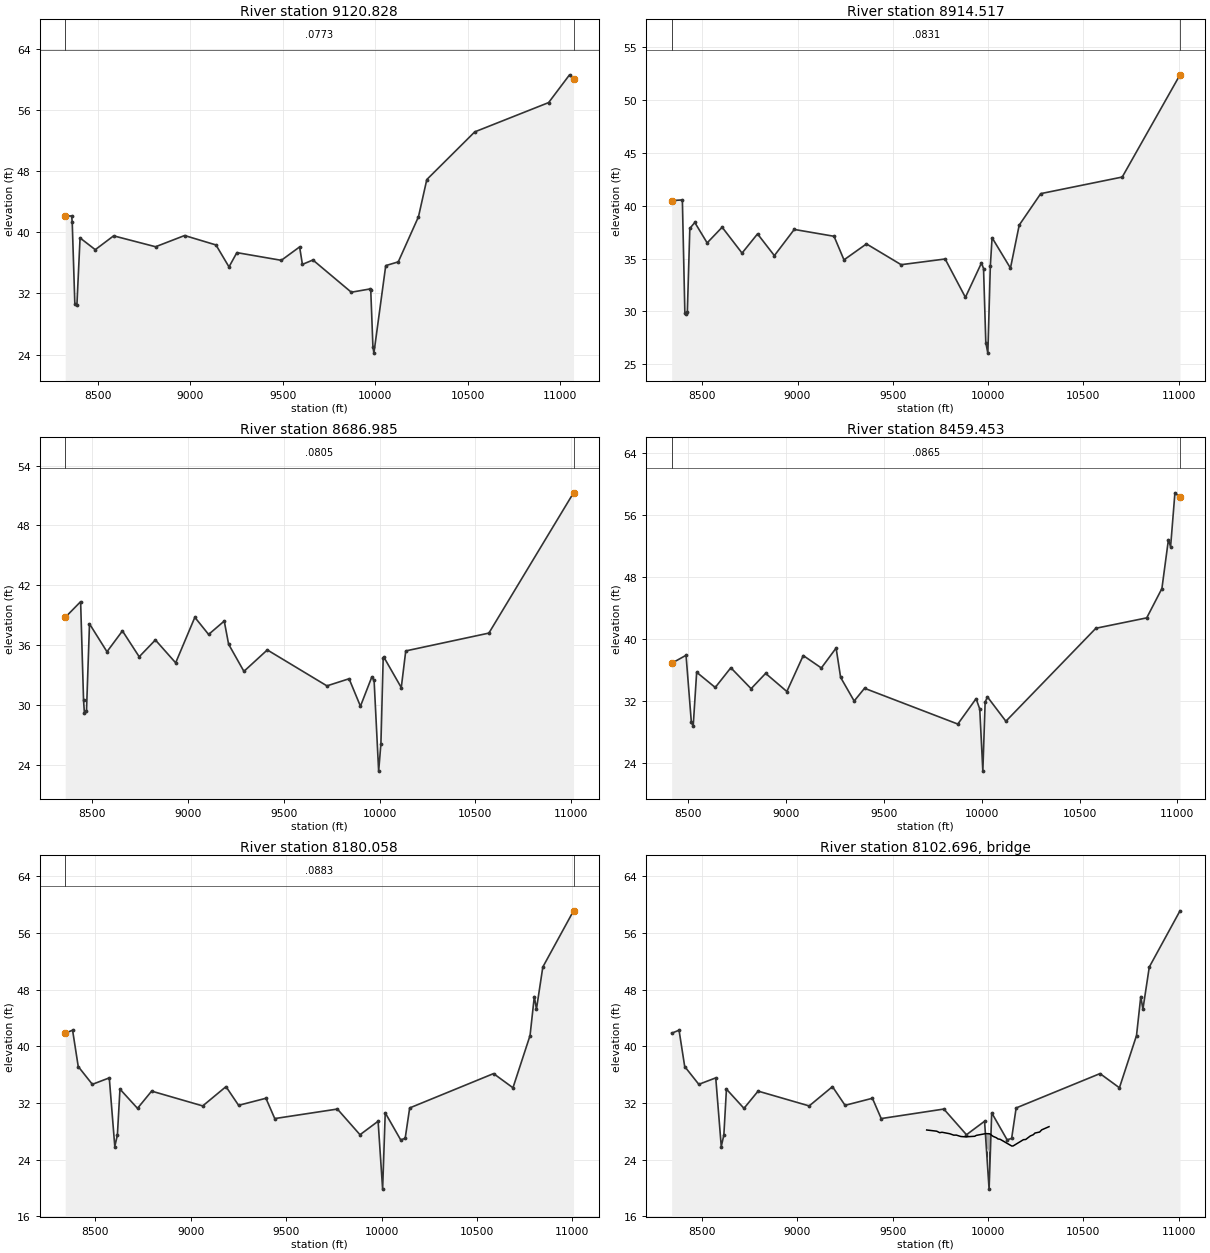
Type RM Length L Ch R = 1 ,9120.828,206.311200,206.311200,206.311200
XS GIS Cut Line= 6
777548.157887578861279.676609695778548.210687995860282.829274148
778815.535387963  860128.1253483778975.010393202860053.382694125
 779299.51048708 859885.03021729779713.520148546859635.539678946
#Sta/Elev= 30
 8325.06 42.12188360.01542.11343 8362.9641.29608 8377.0830.643168388.344 30.5212
8405.31939.242658487.49937.707948586.65339.516838813.29138.090918970.09839.55801
9139.53238.325689209.90835.454439252.40337.322299492.51936.316059591.35638.06785
9606.52535.782779663.18536.359569870.68432.143499973.355 32.57869975.74332.42083
9987.41725.01642 9992.7424.1805810056.6735.6254710124.35 36.1135 10233.542.01189
10278.5646.8778810537.6753.1139810936.6256.9408211049.5760.5712411071.19 59.9747
#Mann= 3 , 0 , 0
 8325.06  0.0773       0 8325.06  0.0773       011071.19  0.0773       0
#XS Ineff= 2 , 0
       09571.682                       0
Bank Sta=8325.06,11071.19
Exp/Cntr=0.3,0.1

Type RM Length L Ch R = 1 ,8914.517,227.532100,227.532100,227.532100
XS GIS Cut Line= 6
777665.299189687861418.013997927778289.025171638860674.546464831
778635.281579792860483.530708358779061.626617432860221.168407574
779271.418137461860120.914439261779792.461167812859891.213115767
#Sta/Elev= 30
8339.14740.482838395.29440.546348408.34729.890618416.47629.72727  8421.429.92966
8434.453 37.85238460.55938.411678525.38936.479738604.14337.963078708.56735.51449
8789.89137.331428878.25735.275278982.68137.75297 9191.5337.105439243.74234.87237
 9361.7636.384479543.77834.416969774.85134.956549881.21131.326749965.68334.58723
9976.413 34.05139988.31427.03609    999926.0475710012.0734.3001910021.2336.97133
10117.7634.0913210163.7338.16558 10276.741.1416610704.5642.7123211007.7952.38498
#Mann= 3 , 0 , 0
8339.147  0.0831       08339.147  0.0831       011007.79  0.0831       0
#XS Ineff= 2 , 0
       0 9583.32        10177.01       0
Bank Sta=8339.147,11007.79
Exp/Cntr=0.3,0.1

Type RM Length L Ch R = 1 ,8686.985,227.532200,227.532200,227.532200
XS GIS Cut Line= 6
777762.357250839861550.830292225778277.083087027860956.052140027
778600.551720679860773.317918614779266.808639616860361.319446236
779516.819026142860229.942106634779903.989938051 860046.39794229
#Sta/Elev= 30
8359.35138.797028439.797 40.37098455.07830.514918459.63429.18061 8470.3629.37478
8486.08338.14989 8577.3335.357248658.00537.443868745.426 34.85398829.92636.53639
8935.72434.246229035.77438.804429107.64537.088039189.17838.429959211.99136.11149
9291.83833.391799413.88635.538289725.04731.939539840.60832.651369899.96429.90026
 9959.3232.835259971.19132.477189994.93423.4016210006.7726.1542810018.5734.69559
10022.3134.8086310112.9731.7669210136.3535.4384610570.0837.2228711011.8451.26922
#Mann= 3 , 0 , 0
8359.351  0.0805       08359.351  0.0805       011011.84  0.0805       0
#XS Ineff= 2 , 0
       09588.209        10181.68       0
Bank Sta=8359.351,11011.84
Exp/Cntr=0.3,0.1

Type RM Length L Ch R = 1 ,8459.453,279.394300,279.394300,279.394300
XS GIS Cut Line= 6
777920.715140194861709.188181549778465.487960517 861114.52535595
778679.135138839860991.436954334779472.970800728860502.723585755
779737.667813927860360.285363689780018.357157022860222.967599988
#Sta/Elev= 30
8414.65936.846068488.14837.877388515.27229.212758524.62928.715728542.39635.68333
8637.32933.71818 8717.0836.266298820.70733.560178895.005  35.539  9003.5 33.1948
9087.17637.844639179.80436.237399255.19338.814139278.27535.020329347.52131.96514
9400.46933.613239877.298  28.9899970.79632.270439989.49530.9275310005.2522.90451
10017.0331.8286510028.8232.4959210123.0829.3524210583.0341.3697210842.9842.71273
10920.6246.50459 10953.952.8243710964.9951.9018310987.17 58.874811013.0858.27379
#Mann= 3 , 0 , 0
8414.659  0.0865       08414.659  0.0865       011013.08  0.0865       0
#XS Ineff= 2 , 0
       09596.557        10190.31       0
Bank Sta=8414.659,11013.08
Exp/Cntr=0.3,0.1

Type RM Length L Ch R = 1 ,8180.058,174.754600,174.754600,174.754600
XS GIS Cut Line= 6
778068.856391519862066.770512283778668.088402629861412.674763754
779020.113847703861111.570123374779646.355288774860721.879631579
779872.768728971860598.827664688780160.321674049860458.107916519
#Sta/Elev= 30
 8341.1441.857518379.84342.27736 8409.4537.147548483.46934.631088572.29135.54331
 8601.2225.844458614.78227.461098628.34433.954998720.32831.237738794.34633.67347
9062.32831.580679184.38634.30562 9250.4831.664989393.87832.662499440.03129.79336
9768.47931.138469887.179 27.50989982.07529.4153610005.8219.8233610019.48 30.6047
10100.3926.7864410124.0426.9942210147.6831.2949810587.5436.1479310689.3434.14476
10778.9541.5309110801.3547.0330310812.5545.2613410845.9551.2093111006.99 59.1479
#Mann= 3 , 0 , 0
 8341.14  0.0883       0 8341.14  0.0883       011006.99  0.0883       0
#XS Ineff= 2 , 0
       09605.714        10200.12       0
Bank Sta=8341.14,11006.99
Exp/Cntr=0.3,0.1

Type RM Length L Ch R = 3 ,8102.696,,,
BEGIN DESCRIPTION:
END DESCRIPTION:
Bridge Culvert--1,0,-1,-1, 0
Deck Dist Width WeirC Skew NumUp NumDn MinLoCord MaxHiCord MaxSubmerge Is_Ogee
66.877300,41.000000,2.6,0, 31, 31, , , 0.95, 0, 0,0,,
 9678.50 9731.07 9746.62 9758.94 9799.52 9820.56 9833.74 9857.34 9881.67 9930.32
 9938.90 9984.60 9984.60 9991.1310009.1710015.4010015.4010026.7410044.3110051.94
10064.1110124.9210132.1510185.7310197.8910222.2210237.5610246.5410270.8710281.68
10320.10
   28.18   28.01   27.80   27.86   27.65   27.45   27.46   27.26   27.21   27.29
   27.42   27.65   27.65   27.67   27.64   27.51   27.51   27.28   27.08   26.92
   26.86   25.91   25.93   26.81   26.84   27.34   27.51   27.75   27.89   28.20
   28.65
 -971.82 -971.99 -972.20 -972.14 -972.35 -972.55 -972.54 -972.74 -972.79 -972.71
 -972.58 -972.35   25.15   25.17   25.14   25.01 -972.49 -972.72 -972.92 -973.08
 -973.14 -974.09 -974.07 -973.19 -973.16 -972.66 -972.49 -972.25 -972.11 -971.80
 -971.35
 9678.50 9731.07 9746.62 9758.94 9799.52 9820.56 9833.74 9857.34 9881.67 9930.32
 9938.90 9984.60 9984.60 9991.1310009.1710015.4010015.4010026.7410044.3110051.94
10064.1110124.9210132.1510185.7310197.8910222.2210237.5610246.5410270.8710281.68
10320.10
   28.18   28.01   27.80   27.86   27.65   27.45   27.46   27.26   27.21   27.29
   27.42   27.65   27.65   27.67   27.64   27.51   27.51   27.28   27.08   26.92
   26.86   25.91   25.93   26.81   26.84   27.34   27.51   27.75   27.89   28.20
   28.65
 -971.82 -971.99 -972.20 -972.14 -972.35 -972.55 -972.54 -972.74 -972.79 -972.71
 -972.58 -972.35   25.15   25.17   25.14   25.01 -972.49 -972.72 -972.92 -973.08
 -973.14 -974.09 -974.07 -973.19 -973.16 -972.66 -972.49 -972.25 -972.11 -971.80
 -971.35
Pier Skew, UpSta & Num, DnSta & Num=  ,9994.53, 2 ,9994.53, 2 , 0 , 0 , 0 ,,
    2.00    2.00
 -972.34   27.66
    2.00    2.00
 -972.34   27.66
Pier Skew, UpSta & Num, DnSta & Num=  ,10005.47, 2 ,10005.47, 2 , 0 , 0 , 0 ,,
    2.00    2.00
 -972.36   27.64
    2.00    2.00
 -972.36   27.64
BR Coef=-1 , 0 , 0 ,, 0 ,,,0.8,0,1,0,
WSPro=,,,, 1 ,,,, 0 ,,,, 0 ,,,,-1 ,-1 ,-1 , 0 , 0 , 0 , 0 , 0
BC Design=,, 0 ,, 0 ,,,,,,

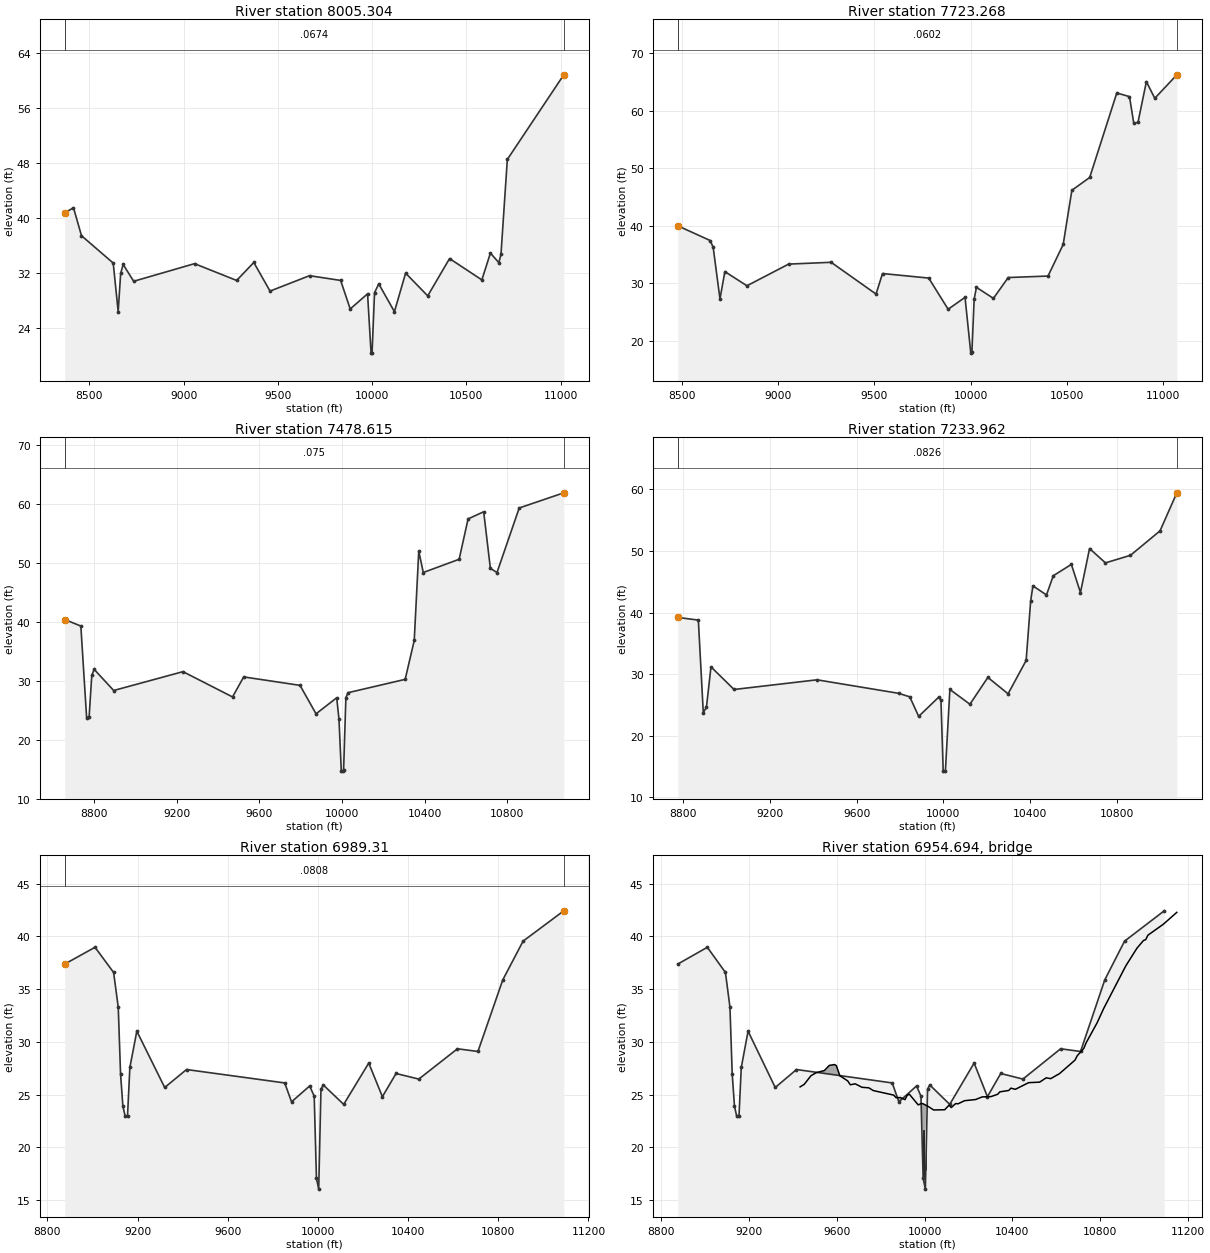
Type RM Length L Ch R = 1 ,8005.304,282.035900,282.035900,282.035900
XS GIS Cut Line= 6
778109.722943604862112.745383382778668.088402629861634.619811252
779003.537129819861325.751559705779548.941228747860981.009297892
779780.666171998860844.795370623780265.294342518860603.434645176
#Sta/Elev= 30
8369.52440.699558415.96741.443998458.30537.370888626.61133.390448652.941 26.3217
8666.10731.870298679.27233.191148735.04930.736169057.91833.302339281.22330.85703
9372.29633.473929458.38229.308199667.78831.552329832.76830.860559883.65726.70884
9975.66228.913499994.16920.315469999.47820.2790110012.6729.0895110035.0930.35585
10118.1426.3147210177.47 31.924310294.6628.6137710410.5434.0430710581.7930.93811
10627.1834.8412510672.0433.4446210683.2634.66919 10716.948.4682211016.25 60.7877
#Mann= 3 , 0 , 0
8369.524  0.0674       08369.524  0.0674       011016.25  0.0674       0
#XS Ineff= 2 , 0
       09609.858        10204.06       0
Bank Sta=8369.524,11016.25
Exp/Cntr=0.3,0.1

Type RM Length L Ch R = 1 ,7723.268,244.652800,244.652800,244.652800
XS GIS Cut Line= 6
778262.972513944862158.720254481778845.661901742861699.454315215
779217.843978107861516.076786935779860.958561957861130.355119035
780172.017266452 860974.80962117780480.037014097860838.071696654
#Sta/Elev= 30
8479.21639.997638647.32437.443828662.92636.266748698.25527.29139 8723.7232.03977
8838.31529.573549054.77233.34137 9275.5433.656979508.71228.134649542.51131.70284
9782.44330.913359883.37425.491189971.08727.56578   1000117.86379 10006.717.98489
10018.5227.2838610030.3429.30124 10118.527.3872810195.3231.0061210402.0631.26501
10480.9136.7608210525.9646.1781810618.5948.4023610759.3363.0998610825.2862.45876
10847.27 57.868710869.25 57.963310912.9665.0704410956.5762.1686211071.0966.25155
#Mann= 3 , 0 , 0
8479.216  0.0602       08479.216  0.0602       011071.09  0.0602       0
#XS Ineff= 2 , 0
       09618.178        10210.62       0
Bank Sta=8479.216,11071.09
Exp/Cntr=0.3,0.1

Type RM Length L Ch R = 1 ,7478.615,244.652700,244.652700,244.652700
XS GIS Cut Line= 6
778487.738550425862179.153530523779009.995416164861820.087147221
779386.197624087861664.162224874780007.739574552861374.020248458
 780337.47541526861237.813215718780646.104259461861118.548165292
#Sta/Elev= 30
8658.07140.396368736.00639.291468763.96723.732148776.10223.935998788.95830.94048
8800.37331.943628894.86328.35307 9230.2331.551969470.00327.260119523.98630.65954
9796.49229.226629874.04624.396639974.03127.12208 9985.1423.43893 9996.2514.68034
10002.1314.6722210007.3714.8163410018.4927.1589210029.61 27.986910305.3830.24538
10349.2236.8416610371.1451.9934410392.9948.3765410566.5950.6218110609.7457.46929
10685.2658.6842210717.63 49.076810749.6848.3696310857.1559.3234211072.7561.89621
#Mann= 3 , 0 , 0
8658.071   0.075       08658.071   0.075       011072.75   0.075       0
#XS Ineff= 2 , 0
       09599.755        10224.02       0
Bank Sta=8658.071,11072.75
Exp/Cntr=0.3,0.1

Type RM Length L Ch R = 1 ,7233.962,244.652700,244.652700,244.652700
XS GIS Cut Line= 6
778625.663163692862255.778315693779117.313529491861944.023933709
779384.265163004861859.600934908779570.556718439861806.961006671
780040.698466778861688.951674312780768.840192497861462.305260032
#Sta/Elev= 30
8773.98939.199988868.81138.769468891.613  23.7218906.15824.621638927.13631.17569
9033.70527.497829416.652 29.07019792.769 26.87849844.57326.304829885.71123.13157
9978.27226.257659988.557 25.75789998.84214.2372810009.1214.3335210029.6727.50566
10122.1825.1044410205.0229.4608310298.2326.7973510381.6232.20851 10402.541.85993
10412.9444.3321110475.5842.8565510506.8945.9733710590.4147.8196210632.3443.24471
10674.3150.3937410747.7748.0631410863.2149.2941210999.6353.2653311077.12 59.4432
#Mann= 3 , 0 , 0
8773.989  0.0826       08773.989  0.0826       011077.12  0.0826       0
#XS Ineff= 2 , 0
       09628.754        10263.91       0
Bank Sta=8773.989,11077.12
Exp/Cntr=0.3,0.1

Type RM Length L Ch R = 1 , 6989.31,75.431100,75.431100,75.431100
XS GIS Cut Line= 6
778724.587131202862341.910842255779210.264214516862222.119175598
779550.107964545862030.712925583779802.068136275862005.984488219
780482.399631202861913.525425583780865.212131202861895.296258926
#Sta/Elev= 30
8877.29137.383689011.61238.97603 9094.0136.586839114.60933.290289124.90926.93476
9135.20823.899119145.50822.929259155.80823.003979166.10827.569479197.00731.01474
9320.60325.671869417.38927.37782 9852.9926.104959883.17924.308189963.66625.82007
9983.70824.848919993.72917.0536310003.7416.0297610013.7525.5141310023.7825.91652
10114.6424.0712810225.66   27.9910286.21 24.800610346.7627.0003110447.6726.47084
10619.2129.3456610710.0129.0906110820.1335.8821810910.2339.5591511090.6542.43395
#Mann= 3 , 0 , 0
8877.291  0.0808       08877.291  0.0808       011090.65  0.0808       0
#XS Ineff= 2 , 0
       09691.961        10339.07       0
Bank Sta=8877.291,11090.65
Exp/Cntr=0.3,0.1

Type RM Length L Ch R = 3 ,6954.694,,,
BEGIN DESCRIPTION:
END DESCRIPTION:
Bridge Culvert--1,0,-1,-1, 0
Deck Dist Width WeirC Skew NumUp NumDn MinLoCord MaxHiCord MaxSubmerge Is_Ogee
17.215550,41.000000,2.6,0, 60, 60, , , 0.95, 0, 0,0,,
 9433.86 9452.43 9483.21 9507.08 9544.01 9566.76 9590.63 9598.97 9614.50 9650.31
 9662.25 9684.57 9715.49 9746.41 9767.03 9859.80 9870.11 9890.72 9911.04 9921.07
 9931.10 9971.22 9983.90 9983.90 9991.2810016.1010016.1010041.4310091.6710111.77
10121.8310141.9310151.9810182.1410232.3810262.5110302.6910332.8310342.8710383.05
10393.1010413.1910473.4610523.6910553.8710574.0010614.2410684.6610694.7210724.91
10734.9710785.2710815.4510916.0610966.2410996.3011006.3211016.3411086.4711148.00
   25.73   25.97   26.79   27.08   27.28   27.77   27.85   27.74   26.79   26.30
   25.93   26.02   25.69   25.64   25.38   24.95   24.71   24.72   24.52   24.93
   25.03   24.02   24.14   24.14   24.15   23.88   23.88   23.54   23.56   24.00
   23.77   24.15   24.12   24.42   24.53   24.78   24.81   25.03   25.26   25.39
   25.61   25.50   26.13   26.18   26.59   26.51   26.99   28.27   28.68   29.39
   29.90   31.81   33.18   37.22   38.88   39.62   39.70   40.12   41.16   42.29
 -974.27 -974.03 -973.21 -972.92 -972.72 -972.23 -972.15 -972.26 -973.21 -973.70
 -974.07 -973.98 -974.31 -974.36 -974.62 -975.05 -975.29 -975.28 -975.48 -975.07
 -974.97 -975.98 -975.86   21.64   21.65   21.38 -976.12 -976.46 -976.44 -976.00
 -976.23 -975.85 -975.88 -975.58 -975.47 -975.22 -975.19 -974.97 -974.74 -974.61
 -974.39 -974.50 -973.87 -973.82 -973.41 -973.49 -973.01 -971.73 -971.32 -970.61
 -970.10 -968.19 -966.82 -962.78 -961.12 -960.38 -960.30 -959.88 -958.84 -957.71
 9433.86 9452.43 9483.21 9507.08 9544.01 9566.76 9590.63 9598.97 9614.50 9650.31
 9662.25 9684.57 9715.49 9746.41 9767.03 9859.80 9870.11 9890.72 9911.04 9921.07
 9931.10 9971.22 9983.90 9983.90 9991.2810016.1010016.1010041.4310091.6710111.77
10121.8310141.9310151.9810182.1410232.3810262.5110302.6910332.8310342.8710383.05
10393.1010413.1910473.4610523.6910553.8710574.0010614.2410684.6610694.7210724.91
10734.9710785.2710815.4510916.0610966.2410996.3011006.3211016.3411086.4711148.00
   25.73   25.97   26.79   27.08   27.28   27.77   27.85   27.74   26.79   26.30
   25.93   26.02   25.69   25.64   25.38   24.95   24.71   24.72   24.52   24.93
   25.03   24.02   24.14   24.14   24.15   23.88   23.88   23.54   23.56   24.00
   23.77   24.15   24.12   24.42   24.53   24.78   24.81   25.03   25.26   25.39
   25.61   25.50   26.13   26.18   26.59   26.51   26.99   28.27   28.68   29.39
   29.90   31.81   33.18   37.22   38.88   39.62   39.70   40.12   41.16   42.29
 -974.27 -974.03 -973.21 -972.92 -972.72 -972.23 -972.15 -972.26 -973.21 -973.70
 -974.07 -973.98 -974.31 -974.36 -974.62 -975.05 -975.29 -975.28 -975.48 -975.07
 -974.97 -975.98 -975.86   21.64   21.65   21.38 -976.12 -976.46 -976.44 -976.00
 -976.23 -975.85 -975.88 -975.58 -975.47 -975.22 -975.19 -974.97 -974.74 -974.61
 -974.39 -974.50 -973.87 -973.82 -973.41 -973.49 -973.01 -971.73 -971.32 -970.61
 -970.10 -968.19 -966.82 -962.78 -961.12 -960.38 -960.30 -959.88 -958.84 -957.71
Pier Skew, UpSta & Num, DnSta & Num=  ,9994.30, 2 ,9994.30, 2 , 0 , 0 , 0 ,,
    2.00    2.00
 -975.87   24.13
    2.00    2.00
 -975.87   24.13
Pier Skew, UpSta & Num, DnSta & Num=  ,10005.70, 2 ,10005.70, 2 , 0 , 0 , 0 ,,
    2.00    2.00
 -975.98   24.02
    2.00    2.00
 -975.98   24.02
BR Coef=-1 , 0 , 0 ,, 0 ,,,0.8,0,1,0,
WSPro=,,,, 1 ,,,, 0 ,,,, 0 ,,,,-1 ,-1 ,-1 , 0 , 0 , 0 , 0 , 0
BC Design=,, 0 ,, 0 ,,,,,,

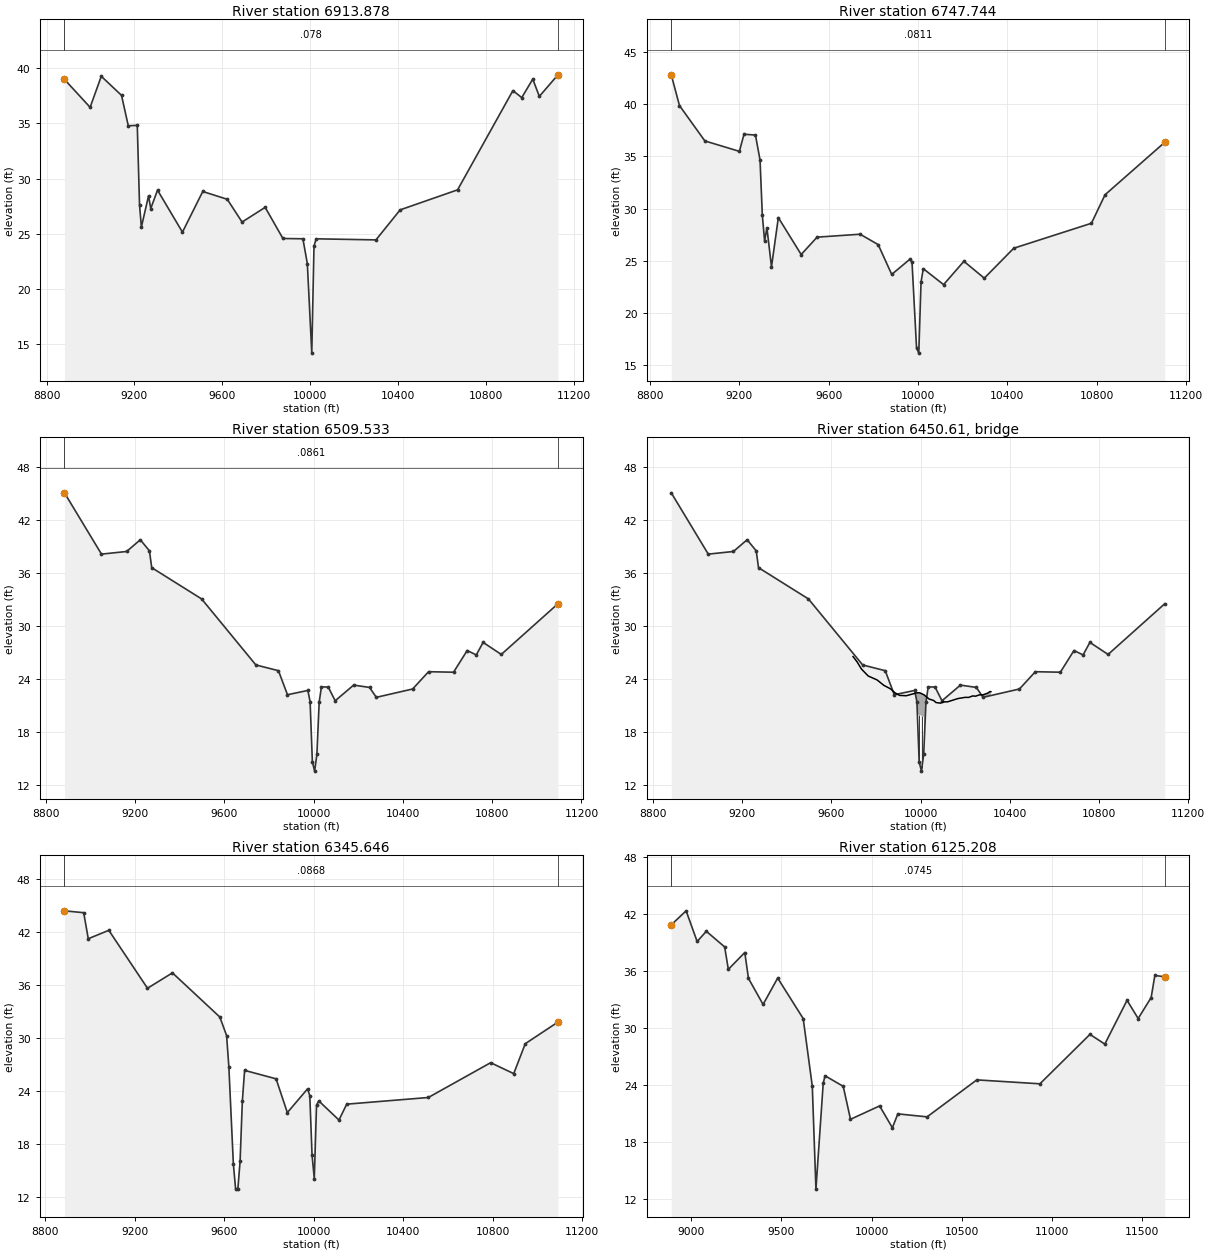
Type RM Length L Ch R = 1 ,6913.878,166.134600,166.134600,166.134600
XS GIS Cut Line= 6
778731.279978812862400.026929602779245.492879868862287.203845814
779442.035047859862158.317092255779546.201714545862116.650425583
779990.038465291862053.429950103780909.633365571861973.685853407
#Sta/Elev= 30
 8881.3738.981278998.14836.453369048.98439.265459141.12537.536659171.839 34.7816
 9212.7934.815959223.02827.638529231.45425.59445 9263.9828.427619274.21727.28044
9304.931 28.95169418.44525.143169510.87128.827189622.44328.120829689.83526.05838
9794.959 27.39059875.80324.568129966.72924.542039986.93422.2971110007.1314.18246
10017.2323.8891910027.3324.5394410299.2224.4410110409.4527.1623710670.84 28.9751
10922.6537.9660210962.9337.3331111013.0339.0057411043.0537.4444211127.7139.39661
#Mann= 3 , 0 , 0
 8881.37   0.078       0 8881.37   0.078       011127.71   0.078       0
#XS Ineff= 2 , 0
       09723.118        10370.28       0
Bank Sta=8881.37,11127.71
Exp/Cntr=0.3,0.1

Type RM Length L Ch R = 1 ,6747.744,238.210800,238.210800,238.210800
XS GIS Cut Line= 6
778729.491690021862460.369247413779285.707896492862327.942365674
779540.402124592862282.940620491780199.449575529862187.706386224
780542.680821178 862116.65593499780893.669621307862030.960833961
#Sta/Elev= 30
8895.77642.822378932.48439.877149046.19936.48636 9200.6835.48804 9221.2737.12798
9272.53337.051759293.03934.657389303.29129.377669313.544 26.89089323.79728.16776
9344.30224.420559374.98929.134719477.09325.602089548.31927.265429741.02627.54754
 9821.7626.550029882.31123.694849963.046 25.13919973.13824.882189993.32216.68279
10003.4116.1507410013.5122.96848 10023.624.2420510114.4322.7166210205.3424.95111
10296.5323.3344210428.4626.2046110775.9828.5957210837.07 31.331611104.0836.35648
#Mann= 3 , 0 , 0
8895.776  0.0811       08895.776  0.0811       011104.08  0.0811       0
#XS Ineff= 2 , 0
       09763.164        10409.01       0
Bank Sta=8895.776,11104.08
Exp/Cntr=0.3,0.1

Type RM Length L Ch R = 1 ,6509.533,163.886700,163.886700,163.886700
XS GIS Cut Line= 6
778743.404265186 862686.79288568779131.523235134862600.432128672
779434.666524784862546.115772145779895.177054289862472.132175549
780015.519896328862440.605973729780914.300004725862269.323421437
#Sta/Elev= 30
 8883.0545.084829048.90738.135769161.66538.43576 9222.9539.764819263.807 38.5103
9274.02136.602029497.69233.056729740.77825.57129 9841.9624.919749882.43322.19431
9973.67922.681389983.83421.411389993.99214.5799310004.1513.53441 10014.3 15.4662
10024.4621.3394410034.6123.0943210065.2623.0577310096.2721.5125610178.9723.28738
10250.1323.0230810280.6221.9009510443.37 22.846910514.6624.8053410626.6924.74894
 10687.827.2096710728.5426.7055110759.0928.1290610840.5726.7629411094.47 32.5097
#Mann= 3 , 0 , 0
 8883.05  0.0861       0 8883.05  0.0861       011094.47  0.0861       0
#XS Ineff= 2 , 0
       09776.677        10439.12       0
Bank Sta=8883.05,11094.47
Exp/Cntr=0.3,0.1

Type RM Length L Ch R = 3 , 6450.61,,,
BEGIN DESCRIPTION:
END DESCRIPTION:
Bridge Culvert--1,0,-1,-1, 0
Deck Dist Width WeirC Skew NumUp NumDn MinLoCord MaxHiCord MaxSubmerge Is_Ogee
56.443350,51.000000,2.6,0, 32, 32, , , 0.95, 0, 0,0,,
 9697.77 9715.53 9735.54 9765.55 9805.57 9835.58 9865.67 9885.76 9905.86 9936.00
 9983.75 9983.75 9986.53 9996.8810016.2510016.2510038.3010059.0110069.3610090.07
10100.4210121.1310167.4410200.6210215.4810233.8010246.9510263.8210279.1610300.68
10311.4410315.42
   26.52   25.93   25.10   24.32   23.87   23.26   22.86   22.41   22.12   22.08
   22.41   22.41   22.42   22.41   22.18   22.18   21.71   21.54   21.31   21.24
   21.38   21.39   21.76   21.90   21.89   22.06   22.03   22.18   22.18   22.37
   22.56   22.54
 -973.48 -974.07 -974.90 -975.68 -976.13 -976.74 -977.14 -977.59 -977.88 -977.92
 -977.59   19.91   19.92   19.91   19.68 -977.82 -978.29 -978.46 -978.69 -978.76
 -978.62 -978.61 -978.24 -978.10 -978.11 -977.94 -977.97 -977.82 -977.82 -977.63
 -977.44 -977.46
 9697.77 9715.53 9735.54 9765.55 9805.57 9835.58 9865.67 9885.76 9905.86 9936.00
 9983.75 9983.75 9986.53 9996.8810016.2510016.2510038.3010059.0110069.3610090.07
10100.4210121.1310167.4410200.6210215.4810233.8010246.9510263.8210279.1610300.68
10311.4410315.42
   26.52   25.93   25.10   24.32   23.87   23.26   22.86   22.41   22.12   22.08
   22.41   22.41   22.42   22.41   22.18   22.18   21.71   21.54   21.31   21.24
   21.38   21.39   21.76   21.90   21.89   22.06   22.03   22.18   22.18   22.37
   22.56   22.54
 -973.48 -974.07 -974.90 -975.68 -976.13 -976.74 -977.14 -977.59 -977.88 -977.92
 -977.59   19.91   19.92   19.91   19.68 -977.82 -978.29 -978.46 -978.69 -978.76
 -978.62 -978.61 -978.24 -978.10 -978.11 -977.94 -977.97 -977.82 -977.82 -977.63
 -977.44 -977.46
Pier Skew, UpSta & Num, DnSta & Num=  ,9994.25, 2 ,9994.25, 2 , 0 , 0 , 0 ,,
    2.00    2.00
 -977.59   22.41
    2.00    2.00
 -977.59   22.41
Pier Skew, UpSta & Num, DnSta & Num=  ,10005.75, 2 ,10005.75, 2 , 0 , 0 , 0 ,,
    2.00    2.00
 -977.67   22.33
    2.00    2.00
 -977.67   22.33
BR Coef=-1 , 0 , 0 ,, 0 ,,,0.8,0,1,0,
WSPro=,,,, 1 ,,,, 0 ,,,, 0 ,,,,-1 ,-1 ,-1 , 0 , 0 , 0 , 0 , 0
BC Design=,, 0 ,, 0 ,,,,,,

Type RM Length L Ch R = 1 ,6345.646,220.438200,220.438200,220.438200
XS GIS Cut Line= 6
778760.834272793 862807.28018805779084.895820341862741.747263174
779327.994860432862700.520100932780009.488392106862631.781417843
780212.780504367862588.864194136780926.561698696862405.901293065
#Sta/Elev= 30
8884.91644.360198970.93744.148328991.37841.202519083.25342.153889256.22635.59536
9367.797 37.33779579.811 32.33659609.98830.234369620.04626.719949640.16415.72631
9650.22212.868389660.28112.85654 9670.3416.018459680.39922.824189690.45726.30191
9831.27925.341959881.57321.517919972.00824.207669982.04323.433599992.07816.70972
10002.11 14.041210012.1522.3790410022.1822.84191 10112.5 20.679110147.1122.47473
10512.0323.2289110790.7627.1692910893.9925.9310710945.6129.3196811091.74 31.7684
#Mann= 3 , 0 , 0
8884.916  0.0868       08884.916  0.0868       011091.74  0.0868       0
#XS Ineff= 2 , 0
       0 9783.46        10463.46       0
Bank Sta=8884.916,11091.74
Exp/Cntr=0.3,0.1

Type RM Length L Ch R = 1 ,6125.208,221.130200,221.130200,221.130200
XS GIS Cut Line= 6
778794.136154711863030.267526999 779310.99397254862938.594789028
779978.520139039862850.741152242780218.402389705862813.053609505
780515.849020153862750.727797151781478.317594856862523.067918658
#Sta/Elev= 30
8889.61140.891848971.92342.363919032.99739.134569083.89340.210139185.50438.56142
9205.77636.201969297.00137.973659317.27335.253819398.36132.50428 9479.21 35.2824
9620.59231.017099671.01423.89416 9691.1713.059159731.48224.19937 9741.5624.99455
9842.34123.884919882.65320.4122810043.9621.8214110114.6319.5203610144.9520.98283
10306.9820.6697610582.54 24.563110932.1324.1495811209.4429.3557511291.6128.33163
11414.8632.9410111476.4831.0253211548.3833.2292111568.9235.5615611623.6835.41658
#Mann= 3 , 0 , 0
8889.611  0.0745       08889.611  0.0745       011623.68  0.0745       0
#XS Ineff= 2 , 0
       09770.892        10552.58       0
Bank Sta=8889.611,11623.68
Exp/Cntr=0.3,0.1

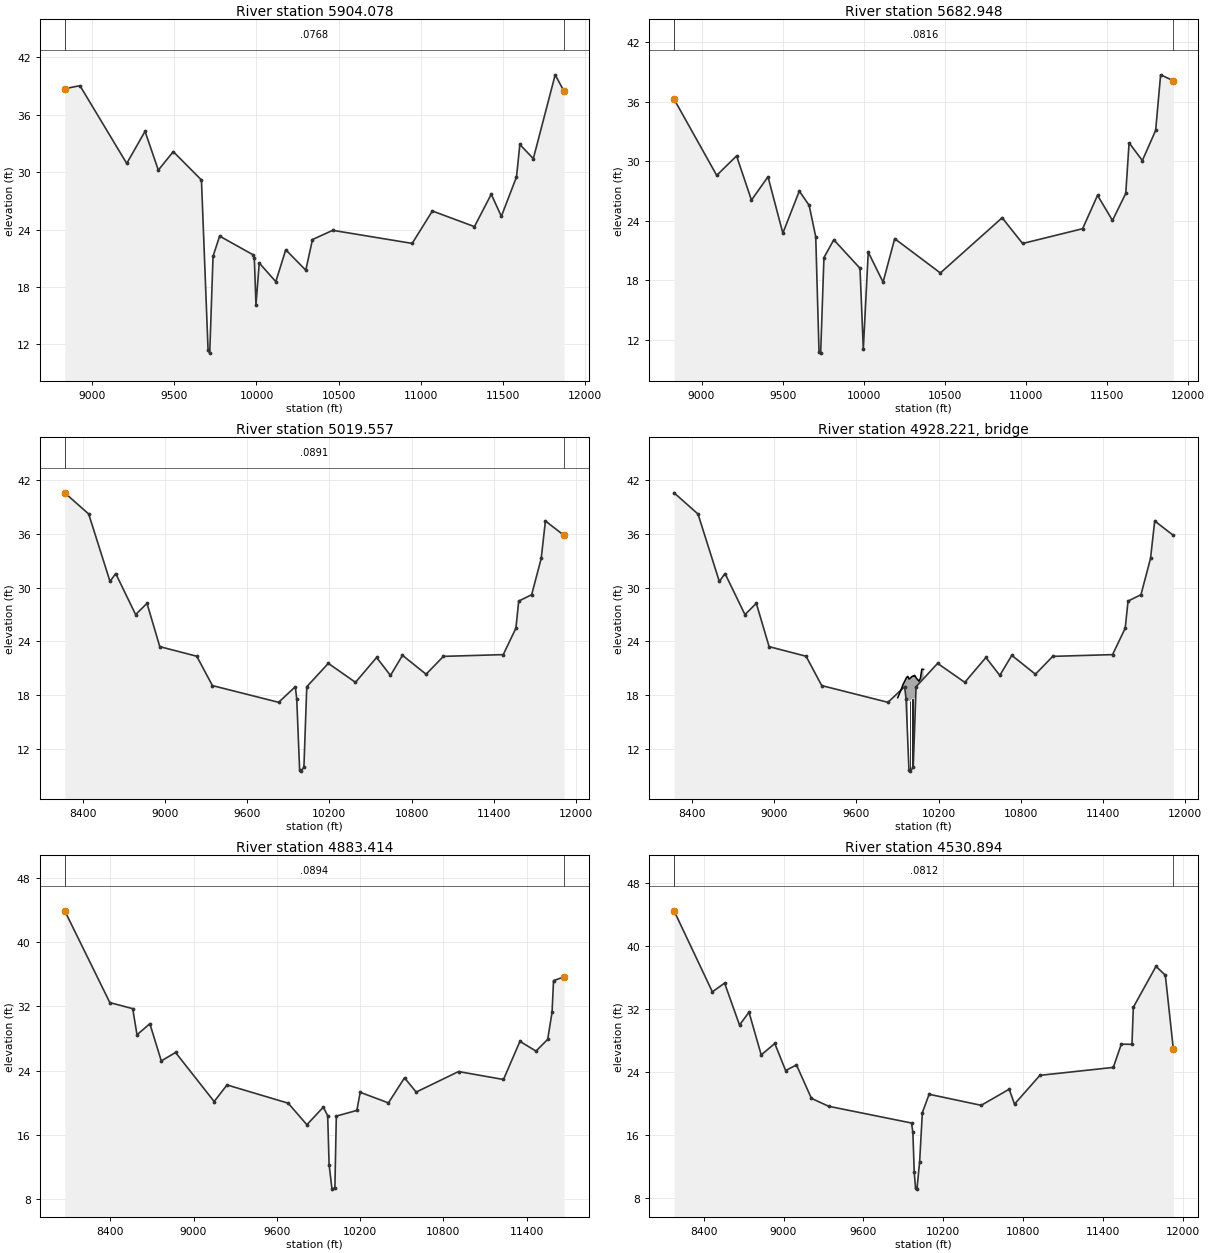
Type RM Length L Ch R = 1 ,5904.078,221.130200,221.130200,221.130200
XS GIS Cut Line= 6
778764.073207855863260.784581333779390.907573611863147.453869879
780013.967901856863071.006732538780188.739105821863042.663073346
780595.799957544862940.846506566781747.712168485862679.806579694
#Sta/Elev= 30
8831.714 38.69628924.31639.012229209.29630.895859320.94434.246039401.99130.19884
9493.10932.128499664.76629.166649705.10111.392519715.18511.098659735.35221.20464
 9775.6323.312359976.82521.386429986.88421.039569996.94416.1518510017.0720.50462
10117.81 18.559110178.4621.8856910300.49 19.7557 10341.422.9537410464.6623.91499
10948.8722.5500211071.9225.9336611328.2624.3017811430.7927.6844411492.3125.37456
 11584.629.48454 11605.132.8741911687.1331.3967111820.4340.1434711874.4838.42423
#Mann= 3 , 0 , 0
8831.714  0.0768       08831.714  0.0768       011874.48  0.0768       0
#XS Ineff= 2 , 0
       09800.857         10637.9       0
Bank Sta=8831.714,11874.48
Exp/Cntr=0.3,0.1

Type RM Length L Ch R = 1 ,5682.948,663.390600,663.390600,663.390600
XS GIS Cut Line= 6
778797.510660172863508.558966652779441.633048147863379.926064521
780169.909154803 863257.85801515780336.835607052863209.848486081
780937.725026965863006.593194976781791.794916868862821.850991264
#Sta/Elev= 30
8830.84936.248289093.63328.565749216.10130.526039307.82726.069699409.66128.42418
9501.259 22.74029602.70526.981779663.572 25.54119704.05222.361689724.26410.77236
9734.36910.640549754.58120.275719815.215 22.06699976.90619.195959997.18711.04713
10027.6620.8228210119.0717.7953610190.6122.1824610472.1418.7249610852.9124.28957
10979.0621.6952711348.7923.1859511440.8726.5479911532.9524.01969 11614.826.74691
11635.2631.8455111717.1130.0611111798.9633.0975111829.66 38.702311908.2338.10925
#Mann= 3 , 0 , 0
8830.849  0.0816       08830.849  0.0816       011908.23  0.0816       0
#XS Ineff= 2 , 0
       09828.981        10716.86       0
Bank Sta=8830.849,11908.23
Exp/Cntr=0.3,0.1

Type RM Length L Ch R = 1 ,5019.557,136.143600,136.143600,136.143600
XS GIS Cut Line= 6
778676.709226966863556.281780809780173.717389882863971.208556622
780325.944137871863629.819372639780579.856843174863423.913142219
781084.572523177863216.551602691781898.237743348 863015.75092648
#Sta/Elev= 30
8269.61840.573048444.25438.212158599.90930.687368641.41731.571848786.69526.99426
8869.71128.246078963.10523.418119232.90722.347579347.054 19.07379830.28617.20784
9952.01418.94962 9962.4817.574719983.413 9.68446 9993.879.53341610014.749.964072
10035.61 18.947410192.7721.5532910391.0619.4355210545.1422.2086410646.4820.20946
 10734.122.4495810906.21 20.341811032.8922.3329811469.2722.5281911561.6525.47793
11582.17 28.496511676.65 29.214211746.2833.2532211776.92 37.435311913.0335.82519
#Mann= 3 , 0 , 0
8269.618  0.0891       08269.618  0.0891       011913.03  0.0891       0
#XS Ineff= 2 , 0
       09437.078        10750.31       0
Bank Sta=8269.618,11913.03
Exp/Cntr=0.3,0.1

Type RM Length L Ch R = 3 ,4928.221,,,
BEGIN DESCRIPTION:
END DESCRIPTION:
Bridge Culvert--1,0,-1,-1, 0
Deck Dist Width WeirC Skew NumUp NumDn MinLoCord MaxHiCord MaxSubmerge Is_Ogee
46.571800,43.000000,2.6,0, 29, 29, , , 0.95, 0, 0,0,,
 9901.58 9911.77 9922.13 9932.49 9937.02 9942.85 9953.21 9963.58 9973.94 9975.18
 9975.25 9975.25 9984.30 9994.6610005.0210013.3410015.3910024.7510024.7510025.75
10036.1110046.4710051.5010056.8410067.2010077.5610087.9210089.6610090.47
   17.72   18.09   18.46   18.87   19.07   19.28   19.57   19.92   20.10   20.10
   20.10   20.10   19.80   19.92   20.08   20.14   20.11   20.20   20.20   20.21
   19.94   19.74   19.66   19.56   19.90   20.90   20.88   20.88   20.88
 -982.28 -981.91 -981.54 -981.13 -980.93 -980.72 -980.43 -980.08 -979.90 -979.90
 -979.90   17.60   17.30   17.42   17.58   17.64   17.61   17.70 -979.80 -979.79
 -980.06 -980.26 -980.34 -980.44 -980.10 -979.10 -979.12 -979.12 -979.12
 9901.58 9911.77 9922.13 9932.49 9937.02 9942.85 9953.21 9963.58 9973.94 9975.18
 9975.25 9975.25 9984.30 9994.6610005.0210013.3410015.3910024.7510024.7510025.75
10036.1110046.4710051.5010056.8410067.2010077.5610087.9210089.6610090.47
   17.72   18.09   18.46   18.87   19.07   19.28   19.57   19.92   20.10   20.10
   20.10   20.10   19.80   19.92   20.08   20.14   20.11   20.20   20.20   20.21
   19.94   19.74   19.66   19.56   19.90   20.90   20.88   20.88   20.88
 -982.28 -981.91 -981.54 -981.13 -980.93 -980.72 -980.43 -980.08 -979.90 -979.90
 -979.90   17.60   17.30   17.42   17.58   17.64   17.61   17.70 -979.80 -979.79
 -980.06 -980.26 -980.34 -980.44 -980.10 -979.10 -979.12 -979.12 -979.12
Pier Skew, UpSta & Num, DnSta & Num=  ,9991.42, 2 ,9991.42, 2 , 0 , 0 , 0 ,,
    2.00    2.00
 -980.12   19.88
    2.00    2.00
 -980.12   19.88
Pier Skew, UpSta & Num, DnSta & Num=  ,10008.58, 2 ,10008.58, 2 , 0 , 0 , 0 ,,
    2.00    2.00
 -979.90   20.10
    2.00    2.00
 -979.90   20.10
BR Coef=-1 , 0 , 0 ,, 0 ,,,0.8,0,1,0,
WSPro=,,,, 1 ,,,, 0 ,,,, 0 ,,,,-1 ,-1 ,-1 , 0 , 0 , 0 , 0 , 0
BC Design=,, 0 ,, 0 ,,,,,,

Type RM Length L Ch R = 1 ,4883.414,352.519300,352.519300,352.519300
XS GIS Cut Line= 6
778629.465218663863682.265803099780128.675083727864047.619467691
780286.155111581864050.769068241780387.938616246863793.978164434
780549.631367058863694.167824417781907.051991075863249.013708025
#Sta/Elev= 30
8072.32343.879298397.09232.452898561.77531.700688592.65328.444118685.28729.82811
8767.62825.195158870.55426.242879148.45620.13862 9241.0922.201349681.74719.93133
 9816.3117.250359934.74919.439639966.11818.381199976.49712.273279997.2549.231733
10018.019.40411510028.3918.3270910176.02 19.026910200.5721.2843310403.7419.96856
 10519.523.0876210603.6921.3153810908.8923.8704411232.3822.8802111350.89 27.6306
11466.6626.4166111550.8527.8754411582.4231.2636611592.9535.1898411668.7735.65669
#Mann= 3 , 0 , 0
8072.323  0.0894       08072.323  0.0894       011668.77  0.0894       0
#XS Ineff= 2 , 0
       09335.018        10647.03       0
Bank Sta=8072.323,11668.77
Exp/Cntr=0.3,0.1

Type RM Length L Ch R = 1 ,4530.894,333.673400,333.673400,333.673400
XS GIS Cut Line= 6
778632.614819199 863820.84822759780237.239843577864136.433137819
780344.231146574864138.789438173780640.808288306864185.706650361
781031.703557491864187.947191596782345.222401381864093.921175107
#Sta/Elev= 30
8177.47744.503828465.27234.193358556.99635.306868669.10329.972478740.44431.59921
8832.16826.170338934.08427.621989015.61624.181649097.14924.896079209.25620.63991
9339.03319.630419961.29617.500569971.45416.321849981.63711.294569991.8219.176663
10002.019.08809610022.3412.5870910042.6818.8230310093.5221.1596710484.8119.75357
10695.0321.80748 10735.119.9051910925.5923.5675711477.2124.5786411537.3527.53642
11617.5427.5150811627.5632.2285711797.9637.4380611868.1336.3082311928.4926.87499
#Mann= 3 , 0 , 0
8177.477  0.0812       08177.477  0.0812       011928.49  0.0812       0
#XS Ineff= 2 , 0
       09468.104        10531.05       0
Bank Sta=8177.477,11928.49
Exp/Cntr=0.3,0.1