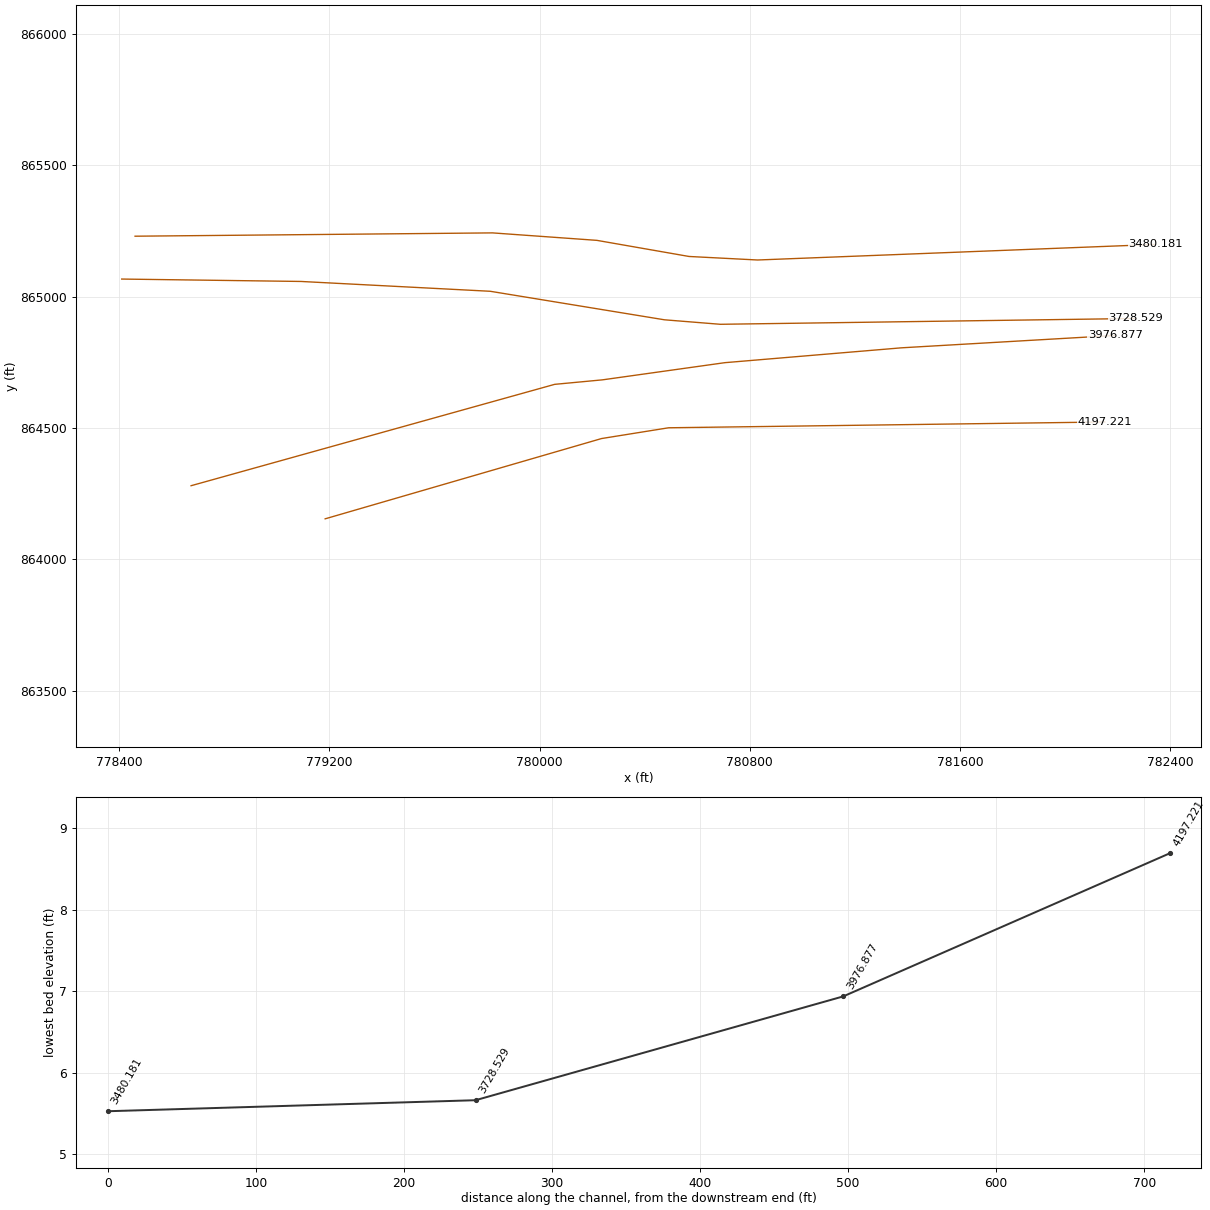
HEC-RAS study 16031_ras.prj: 16031

--- 16031_ras.g01 (geometry) --- (continued)

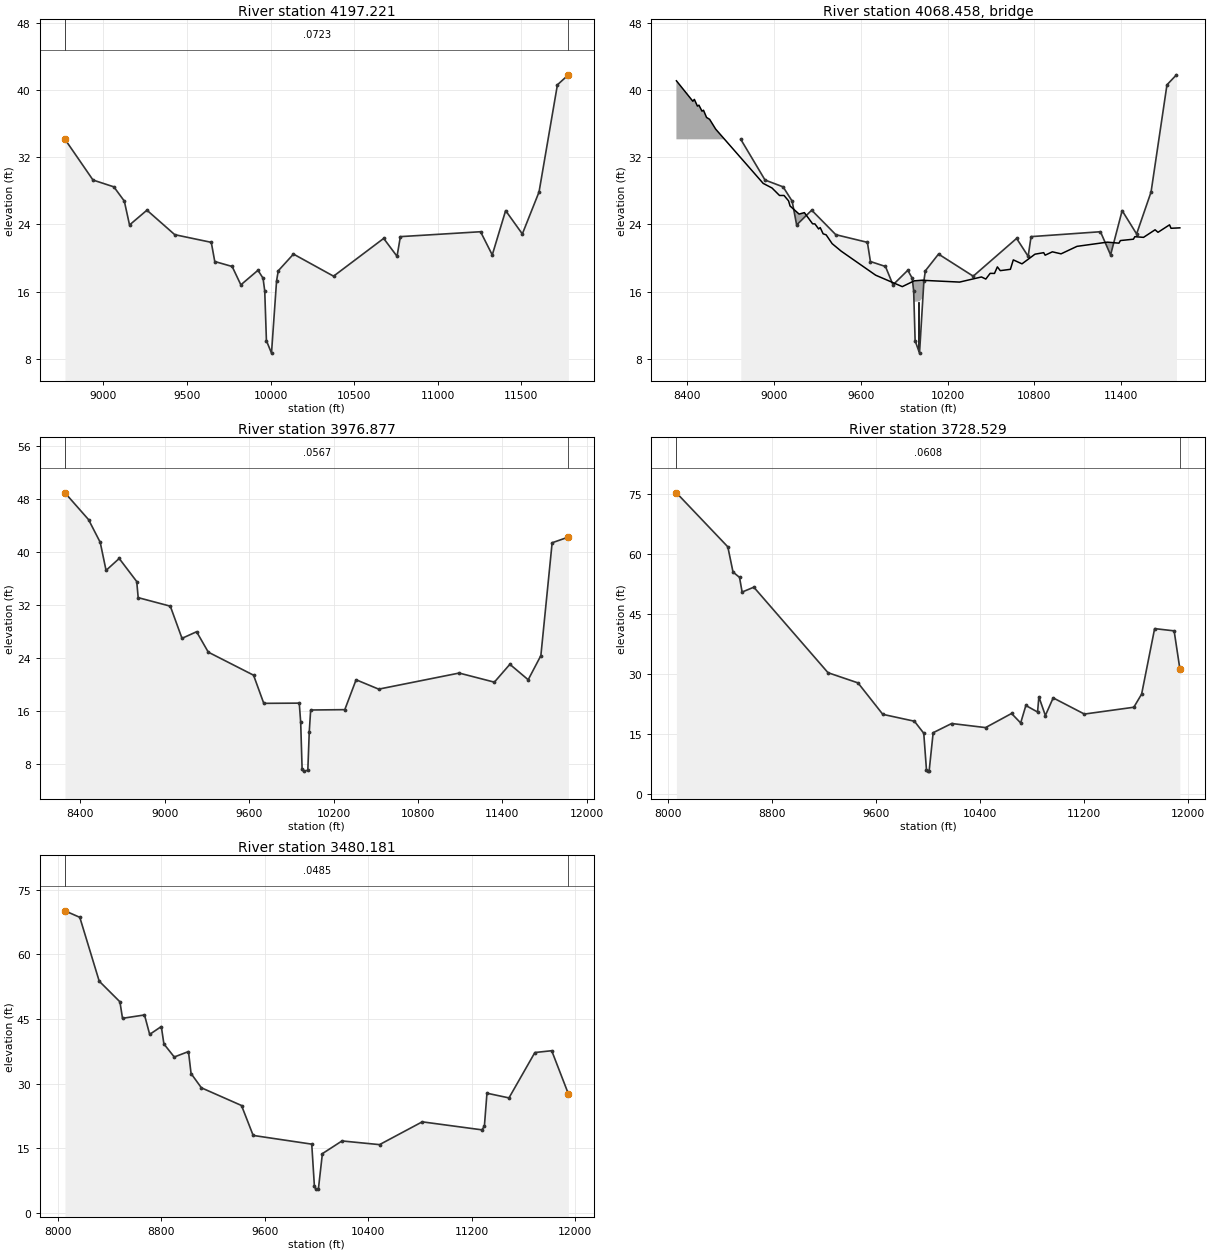
Type RM Length L Ch R = 1 ,4197.221,220.343500,220.343500,220.343500
XS GIS Cut Line= 4
 779183.79491663864154.705886617780235.761502653 864460.21714066
780490.879147768864501.161947876782150.718641251864523.209151804
#Sta/Elev= 30
8769.38434.121198937.24929.278329062.20828.465439124.687 26.77429155.92623.93358
9260.05825.691739426.66922.779069645.346 21.86659666.17219.587779770.304 18.9954
 9822.3716.810179924.81218.545199955.196 17.60299965.32416.090159975.45210.16937
10005.848.69167610036.22 17.293410046.3518.4846710137.3220.4707910377.3417.84252
10677.3722.3339210757.3720.2051910777.3822.5459411257.4223.1292111327.4320.36767
11407.4325.6411211507.4422.8644611607.4527.8584311717.4640.6024311783.1841.78915
#Mann= 3 , 0 , 0
8769.384  0.0723       08769.384  0.0723       011783.18  0.0723       0
#XS Ineff= 2 , 0
       09616.695        10542.68       0
Bank Sta=8769.384,11783.18
Exp/Cntr=0.3,0.1

Type RM Length L Ch R = 3 ,4068.458,,,
BEGIN DESCRIPTION:
END DESCRIPTION:
Bridge Culvert--1,0,-1,-1, 0
Deck Dist Width WeirC Skew NumUp NumDn MinLoCord MaxHiCord MaxSubmerge Is_Ogee
54.671750,111.000000,2.6,0, 60, 60, , , 0.95, 0, 0,0,,
 8324.29 8437.92 8448.46 8469.53 8480.07 8501.14 8511.68 8532.75 8553.82 8595.96
 8924.35 8985.58 9037.57 9068.76 9100.03 9110.36 9172.75 9209.45 9266.33 9282.40
 9307.93 9318.87 9339.12 9359.92 9401.51 9463.90 9702.49 9886.64 9969.30 9969.30
10029.1610030.7010030.7010283.0610434.2410464.2710494.3110524.3510544.3710564.39
10634.4810654.5010714.5710804.6810864.7510874.7610924.8210984.8911095.0211305.22
11385.2311395.2311485.2511495.2511555.2611635.2711655.2711735.2811745.2811806.49
   41.08   38.65   38.87   38.07   38.18   37.47   37.58   36.72   36.50   35.33
   28.88   28.33   27.44   27.44   26.80   26.19   25.23   25.40   24.07   24.06
   23.46   23.62   22.88   22.76   21.71   20.82   17.96   16.60   17.29   17.29
   17.37   17.35   17.35   17.14   17.75   17.50   18.18   18.17   18.95   18.50
   18.66   19.78   19.31   20.46   20.64   20.34   20.74   20.50   21.39   21.89
   21.77   22.08   22.24   22.54   22.46   23.36   23.06   23.95   23.54   23.59
 -958.92 -961.35 -961.13 -961.93 -961.82 -962.53 -962.42 -963.28 -963.50 -964.67
 -971.12 -971.67 -972.56 -972.56 -973.20 -973.81 -974.77 -974.60 -975.93 -975.94
 -976.54 -976.38 -977.12 -977.24 -978.29 -979.18 -982.04 -983.40 -982.71   14.79
   14.87   14.85 -982.65 -982.86 -982.25 -982.50 -981.82 -981.83 -981.05 -981.50
 -981.34 -980.22 -980.69 -979.54 -979.36 -979.66 -979.26 -979.50 -978.61 -978.11
 -978.23 -977.92 -977.76 -977.46 -977.54 -976.64 -976.94 -976.05 -976.46 -976.41
 8324.29 8437.92 8448.46 8469.53 8480.07 8501.14 8511.68 8532.75 8553.82 8595.96
 8924.35 8985.58 9037.57 9068.76 9100.03 9110.36 9172.75 9209.45 9266.33 9282.40
 9307.93 9318.87 9339.12 9359.92 9401.51 9463.90 9702.49 9886.64 9969.30 9969.30
10029.1610030.7010030.7010283.0610434.2410464.2710494.3110524.3510544.3710564.39
10634.4810654.5010714.5710804.6810864.7510874.7610924.8210984.8911095.0211305.22
11385.2311395.2311485.2511495.2511555.2611635.2711655.2711735.2811745.2811806.49
   41.08   38.65   38.87   38.07   38.18   37.47   37.58   36.72   36.50   35.33
   28.88   28.33   27.44   27.44   26.80   26.19   25.23   25.40   24.07   24.06
   23.46   23.62   22.88   22.76   21.71   20.82   17.96   16.60   17.29   17.29
   17.37   17.35   17.35   17.14   17.75   17.50   18.18   18.17   18.95   18.50
   18.66   19.78   19.31   20.46   20.64   20.34   20.74   20.50   21.39   21.89
   21.77   22.08   22.24   22.54   22.46   23.36   23.06   23.95   23.54   23.59
 -958.92 -961.35 -961.13 -961.93 -961.82 -962.53 -962.42 -963.28 -963.50 -964.67
 -971.12 -971.67 -972.56 -972.56 -973.20 -973.81 -974.77 -974.60 -975.93 -975.94
 -976.54 -976.38 -977.12 -977.24 -978.29 -979.18 -982.04 -983.40 -982.71   14.79
   14.87   14.85 -982.65 -982.86 -982.25 -982.50 -981.82 -981.83 -981.05 -981.50
 -981.34 -980.22 -980.69 -979.54 -979.36 -979.66 -979.26 -979.50 -978.61 -978.11
 -978.23 -977.92 -977.76 -977.46 -977.54 -976.64 -976.94 -976.05 -976.46 -976.41
Pier Skew, UpSta & Num, DnSta & Num=  ,10000.00, 2 ,10000.00, 2 , 0 , 0 , 0 ,,
    3.00    3.00
 -982.84   17.16
    3.00    3.00
 -982.84   17.16
BR Coef=-1 , 0 , 0 ,, 0 ,,,0.8,0,1,0,
WSPro=,,,, 1 ,,,, 0 ,,,, 0 ,,,,-1 ,-1 ,-1 , 0 , 0 , 0 , 0 , 0
BC Design=,, 0 ,, 0 ,,,,,,

Type RM Length L Ch R = 1 ,3976.877,248.348400,248.348400,248.348400
XS GIS Cut Line= 6
 778673.55962643864280.689908907780057.131399482864666.417390779
780238.798844278864683.533787593780704.789861768864748.907835469
781377.837693602864805.504314527782190.359399468864852.607022122
#Sta/Elev= 30
8290.40848.888068458.00544.853798541.056 41.42438582.58137.193938676.01338.99238
8800.58935.515868810.97133.086859039.36131.801419122.41126.952379226.22527.94917
9309.27624.872629631.09821.397929703.76717.154259956.09617.185629966.22514.26714
9976.3567.2118429986.4936.93629310016.917.06414110027.0412.8342910037.1816.15017
10279.7716.2028710360.1520.7072310520.7419.2948211092.6821.71933 11343.1 20.3482
11453.2923.04024 11583.520.7112311673.6524.3519311753.7941.3608111869.3442.21696
#Mann= 3 , 0 , 0
8290.408  0.0567       08290.408  0.0567       011869.34  0.0567       0
#XS Ineff= 2 , 0
       09684.778        10606.19       0
Bank Sta=8290.408,11869.34
Exp/Cntr=0.3,0.1

Type RM Length L Ch R = 1 ,3728.529,248.348400,248.348400,248.348400
XS GIS Cut Line= 6
778409.728561384865067.123782162779091.579942162865058.004560072
779812.045764303865020.603721011780475.105172145864912.069744313
 780687.49176704864894.965622478782268.879066972864917.131660624
#Sta/Elev= 30
8064.33475.282468459.61761.772078499.62455.46964 8549.6454.127348569.64650.45913
8659.67551.676699230.24330.282369460.69127.735289651.45119.867199894.40618.14868
9966.39215.138669987.0596.0571679997.3925.66160410007.735.68967410038.6915.27555
10181.0117.5747510441.5616.5523910641.5720.0819210711.5717.7132910751.5822.08426
 10841.620.44696 10851.624.2523210901.6119.5750710961.6223.9849511201.6619.93613
11581.7321.6422911641.7424.9291211741.76 41.313611891.7940.7509211935.6731.27671
#Mann= 3 , 0 , 0
8064.334  0.0608       08064.334  0.0608       011935.67  0.0608       0
#XS Ineff= 2 , 0
       0                10610.78       0
Bank Sta=8064.334,11935.67
Exp/Cntr=0.3,0.1

Type RM Length L Ch R = 1 ,3480.181,0.000000,0.000000,0.000000
XS GIS Cut Line= 6
778460.343589728 865230.20339373 779820.73753724865242.802415524
780217.831255008865214.379959136780568.469919726 865153.09017131
 780829.56656881865139.650371805782343.817262341865198.902334157
#Sta/Elev= 30
8053.83170.076198168.55568.566598318.64253.761338478.73548.97564 8498.7445.14855
8668.76945.924148708.77541.417028798.78243.240658818.78239.200938898.78236.17217
9008.78237.434329028.78332.336989108.78729.024449418.87924.922219509.00917.98046
9961.90815.95897 9982.426.1788259992.7545.52634810013.425.59574410044.1813.75929
10195.68 16.702710486.0215.8467710816.1221.1338911276.5119.2796911296.5320.06159
11316.5527.7743311486.7526.6842611687.0137.2113411817.1837.6297211946.1727.61083
#Mann= 3 , 0 , 0
8053.831  0.0485       08053.831  0.0485       011946.17  0.0485       0
#XS Ineff= 2 , 0
       0                10750.45       0
Bank Sta=8053.831,11946.17
Exp/Cntr=0.3,0.1